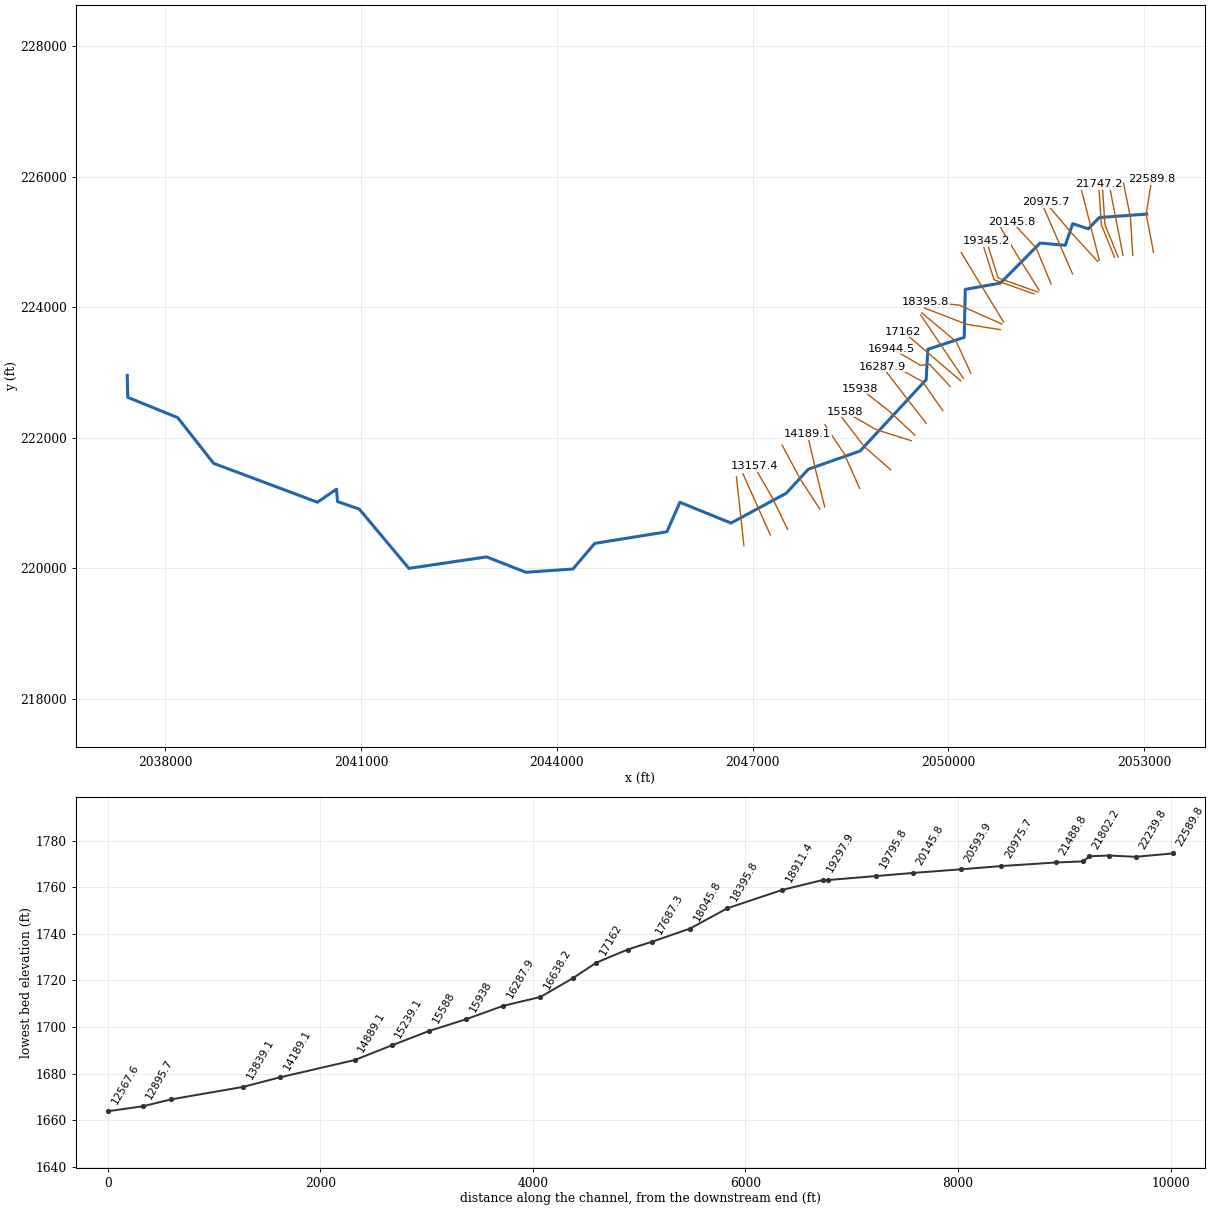
--- STONYCK.prj (project) ---

Proj Title=STONYCK
Current Plan=p01
Default Exp/Contr=0,0
English Units
Geom File=g01
Flow File=f01
Plan File=p01
BEGIN DESCRIPTION:
END DESCRIPTION:
DSS Export Rating Curves= 0
DSS Export Rating Curve Sorted= 0
DSS Export Volume Flow Curves= 0
DXF OffsetX= 0
DXF OffsetY= 0
DXF ScaleX= 0
DXF ScaleY= 0

--- STONYCK.p01 (plan) ---

Plan Title=Floodplain
Program Version=4.00
Geom File=g01
Flow File=f01
K Sum by GR=0
Std Step Tol=0.01
Critical Tol=0.01
Num of Std Step Trials=20
Max Error Tol=0.3
Flow Tol Ratio=0.001
Split Flow NTrial=30
Split Flow Tol=0.02
Split Flow Ratio=0.02
Log Output Level=0
Friction Slope Method=1
Unsteady Friction Slope Method=2
Unsteady Bridges Friction Slope Method=1
Global Log Level=0
CheckData=False
Run HTab=0
Run UNet=0
Run PostProcess=0
UNET Theta=0
UNET Theta Warmup=0
UNET ZTol=0
UNET ZSATol=0
UNET MxIter=0
UNET MaxInSteps=0
UNET DtIC=0
UNET DtMin=0
UNET MaxCRTS=0
UNET WFStab=0
UNET SFStab=0
UNET WFX=0
UNET SFX=0
UNET DSS MLevel=0
UNET DZMax Abort=0
UNET Convert EG Bridges=0
UNET Use Existing IB Tables=0
UNET Froude Limit=0
UNET Froude Power=0
Write IC File=0
Echo Input=False
Echo Output=False
Write Detailed=0

--- STONYCK.f01 (steady flow) ---

Flow Title=2010 USGS WV Regression Equation
Program Version=4.00
Number of Profiles=1
Profile Names=P100yr
River Rch & RM=STONYCK,Main      ,22589.8
784.3802
River Rch & RM=STONYCK,Main      ,19795.8
839.3960
River Rch & RM=STONYCK,Main      ,19297.9
 849.243
River Rch & RM=STONYCK,Main      ,18395.8
967.9608
River Rch & RM=STONYCK,Main      ,18395.8
934.3857
River Rch & RM=STONYCK,Main      ,15588
1039.808
River Rch & RM=STONYCK,Main      ,10478.5
1149.854
River Rch & RM=STONYCK,Main      ,7299.5
1269.727
River Rch & RM=STONYCK,Main      ,543.1
1350.357
River Rch & RM=STONYCK,Main      ,277.9
1350.824
Boundary for River Rch & Prof#=STONYCK,Main      ,1
Up Type=0
Dn Type=3
Dn Slope=0.041923

--- STONYCK.g01 (geometry) ---

Geom Title=LiDAR
Program Version=4.10

River Reach=STONYCK         ,Main
Reach XY= 30
     2053042.726      225426.475     2052313.559      225373.523
     2052147.761       225200.78     2051908.177      225278.905
     2051792.726      224948.176     2051407.309      224982.899
      2050799.67      224370.051     2050260.608      224272.829
     2050244.115      223537.586     2049686.823      223355.294
     2049660.781      222890.017     2048648.629      221797.135
     2047854.358      221517.621     2047515.816      221149.565
     2046669.462      220692.968     2045886.476      221010.676
     2045685.955      220559.287     2044579.184      220381.336
     2044245.851      219988.975     2043525.365      219938.627
     2042922.066      220174.739     2041731.962      219998.523
     2040970.831      220906.356     2040638.212      221021.961
     2040620.851      221211.197     2040329.184      221012.412
     2038738.906       221607.03     2038187.691      222307.551
     2037422.066      222619.183      2037413.82      222955.554

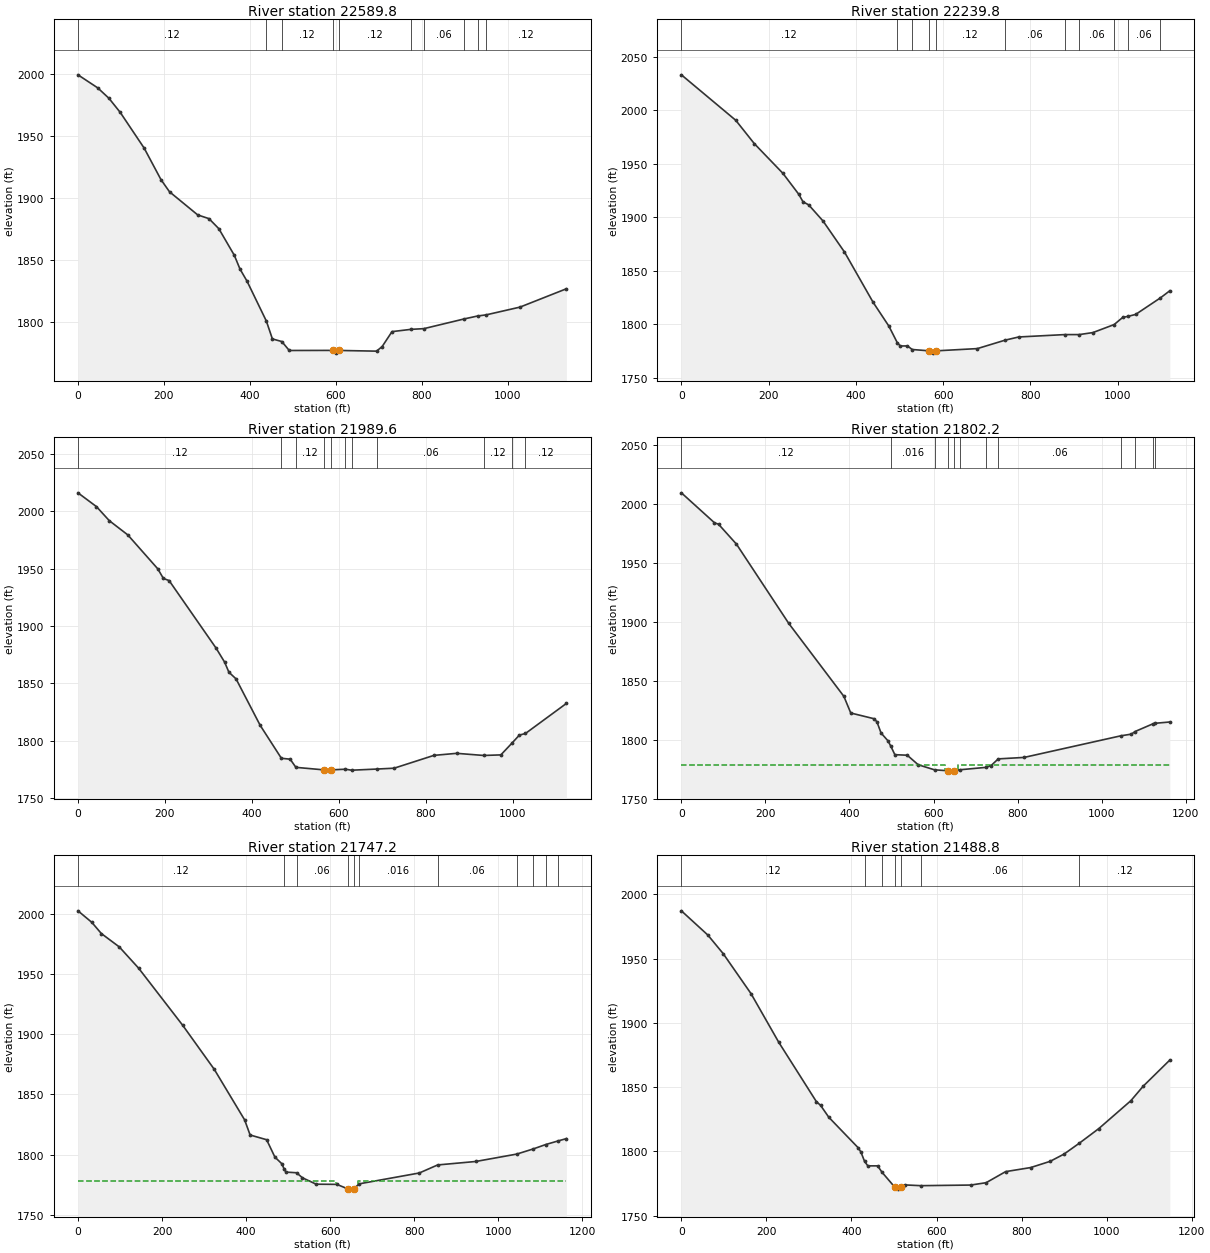
Type RM Length L Ch R = 1 ,22589.8 ,342.5,350,350.9
XS GIS Cut Line= 3
     2053147.209      224839.823      2053032.92      225428.436
     2053120.299      225957.682
#Sta/Elev= 30
       0 1999.38    45.9 1988.86    72.1 1980.42    98.3 1969.05     154 1940.17
   193.3  1914.6     213 1904.91   278.5 1886.25   304.7 1883.24   327.6 1875.14
   363.7 1853.61   376.8 1842.56   393.2 1832.76  438.161800.525   452.2  1786.1
  474.041783.995   491.5 1776.76   592.1 1776.84   599.6 1774.63   607.1 1776.79
   694.5 1776.23   707.5 1779.95   730.4    1792  774.521793.828  804.461794.396
  897.891802.218  929.341804.604  949.371805.531  1028.1  1811.8    1136  1826.6
#Mann= 10 ,-1 , 0
       0     .12       0  438.16    .016       0  474.04     .12       0
   592.1    .045       0   607.1     .12       0  774.52    .016       0
  804.46     .06       0  897.89     .12       0  929.34     .06       0
  949.37     .12       0
Bank Sta=592.1,607.1
XS Rating Curve= 0 ,0
Exp/Cntr=0.3,0.1

Type RM Length L Ch R = 1 ,22239.8 ,245,250.3,248.6
XS GIS Cut Line= 3
     2052827.833      224794.861     2052793.044      225370.919
     2052685.541      225902.405
#Sta/Elev= 30
       0 2033.24   124.6 1990.76   167.2 1968.91   232.8 1941.13   268.9 1921.69
   278.7 1914.61   291.8  1911.7   324.6 1896.66   373.8 1867.64   439.4 1820.67
   475.5 1798.42  494.881782.867   501.7 1779.86   518.1 1779.89  528.991776.559
  568.351775.298   577.1 1773.17  582.461775.272   678.4 1777.41  741.821785.286
   773.1 1788.26  878.111790.484  911.841790.501     943 1792.36  991.761799.854
  1011.6  1806.6  1022.81807.454    1041 1809.32 1097.711824.764  1119.4 1831.45
#Mann= 11 ,-1 , 0
       0     .12       0  494.88    .016       0  528.99     .12       0
  568.35    .045       0  582.46     .12       0  741.82     .06       0
  878.11    .016       0  911.84     .06       0  991.76    .016       0
  1022.8     .06       0 1097.71     .12       0
Bank Sta=568.35,582.46
XS Rating Curve= 0 ,0
Exp/Cntr=0.3,0.1

Type RM Length L Ch R = 1 ,21989.6 ,183.7,187.4,183
XS GIS Cut Line= 2
     2052677.663      224797.756     2052462.819      225900.187
#Sta/Elev= 30
       0 2015.92    42.6  2003.9      72  1991.7   114.6  1979.3   183.4 1949.84
   196.5 1941.39   209.6 1939.56   317.6 1880.78   337.3 1868.54   347.1 1859.78
   363.5 1854.03   419.1 1813.51  467.791784.895   487.9 1784.13  501.161777.005
   566.5 1774.78   576.3 1773.72  581.091774.802  615.051775.383  629.461774.526
  688.691775.554     727 1776.27   818.6 1787.43     871 1789.21  932.94 1787.35
   972.5 1787.85  998.911798.458  1015.1 1805.09    10291806.473  1123.2 1832.64
#Mann= 11 ,-1 , 0
       0     .12       0  467.79    .016       0  501.16     .12       0
   566.5    .045       0  581.09     .12       0  615.05     .06       0
  629.46     .12       0  688.69     .06       0  932.94     .12       0
  998.91    .016       0    1029     .12       0
Bank Sta=566.5,581.09
XS Rating Curve= 0 ,0
Exp/Cntr=0.3,0.1

Type RM Length L Ch R = 1 ,21802.2 ,60.9,55,54.9
XS GIS Cut Line= 3
     2052603.444      224768.676     2052402.055      225263.468
     2052359.521      225890.204
#Sta/Elev= 30
       0 2009.34    78.7 1983.96    88.5  1982.7   131.1 1965.83   255.6  1898.6
   386.7  1836.8   403.1 1822.68   458.8 1817.81   465.4 1815.18   475.2 1805.74
   491.6 1799.12  498.741794.316     508 1787.36   537.5  1786.9   563.6 1778.82
  602.441774.514   635.6 1773.68   642.2 1773.41   648.7 1773.57  663.551774.577
  724.47 1776.59   737.1 1778.15  754.081783.784   815.6 1785.03 1045.42 1803.32
  1070.8 1804.77 1079.741806.993 1121.921813.477 1126.511813.938  1162.4 1815.07
#Mann= 12 ,-1 , 0
       0     .12       0  498.74    .016       0  602.44     .12       0
   635.6    .045       0   648.7     .12       0  663.55     .06       0
  724.47     .12       0  754.08     .06       0 1045.42    .016       0
 1079.74     .12       0 1121.92     .06       0 1126.51     .12       0
#XS Ineff= 2 , 0
          628.14 1778.55  657.75          1778.2
Permanent Ineff=
       F       F
Bank Sta=635.6,648.7
XS Rating Curve= 0 ,0
Exp/Cntr=0.3,0.1

Type RM Length L Ch R = 1 ,21747.2 ,253.1,258.4,259.9
XS GIS Cut Line= 3
     2052548.757       224764.77     2052347.368      225259.562
     2052304.833      225886.298
#Sta/Elev= 30
       0 2002.67    32.8 1993.14    55.7 1983.76    98.3 1972.67   144.2 1955.04
   249.1 1907.54   324.5 1870.77   396.6 1828.81   409.7 1816.22     449 1812.29
   468.7 1797.83     485 1792.37  490.351788.184   494.9 1785.37  520.131784.817
   534.2 1780.64   566.9  1775.3     616 1775.16   642.2 1771.43   655.3  1771.2
   656.81771.552  669.171775.589   812.3 1784.62  856.021791.312   946.4 1794.18
 1044.321800.352 1083.661804.649 1113.261808.297 1142.871811.306  1162.4 1813.22
#Mann= 11 ,-1 , 0
       0     .12       0  490.35    .016       0  520.13     .06       0
   642.2    .045       0   656.8     .06       0  669.17    .016       0
  856.02     .06       0 1044.32    .016       0 1083.66     .06       0
 1113.26     .12       0 1142.87     .06       0
#XS Ineff= 2 , 0
          613.45 1777.71  667.59         1778.02
Permanent Ineff=
       F       F
Bank Sta=642.2,656.8
XS Rating Curve= 0 ,0
Exp/Cntr=0.3,0.1

Type RM Length L Ch R = 1 ,21488.8 ,465,513.1,480.9
XS GIS Cut Line= 2
      2052315.25      224717.461     2052033.132      225830.742
#Sta/Elev= 30
       0 1987.13    62.2  1968.3    98.2 1953.89   163.6 1922.81     229  1884.9
   317.4 1838.78   327.2  1835.9   346.8 1826.55   415.5 1802.97   422.1 1799.62
  430.731792.324   438.4 1788.82   461.4 1788.82  472.081783.723   501.3 1772.45
   510.4 1770.73   516.3  1772.6   526.8 1773.98  563.15 1773.42   680.6  1773.9
   716.6 1775.73   762.4 1784.34   821.3  1787.5   867.1 1792.34   899.8 1797.99
  935.871806.484   981.6 1817.83  1056.9 1839.49  1086.3 1850.91  1148.5  1871.1
#Mann= 7 ,-1 , 0
       0     .12       0  430.73    .016       0  472.08     .12       0
   501.3    .045       0   516.3     .12       0  563.15     .06       0
  935.87     .12       0
Bank Sta=501.3,516.3
XS Rating Curve= 0 ,0
Exp/Cntr=0.3,0.1

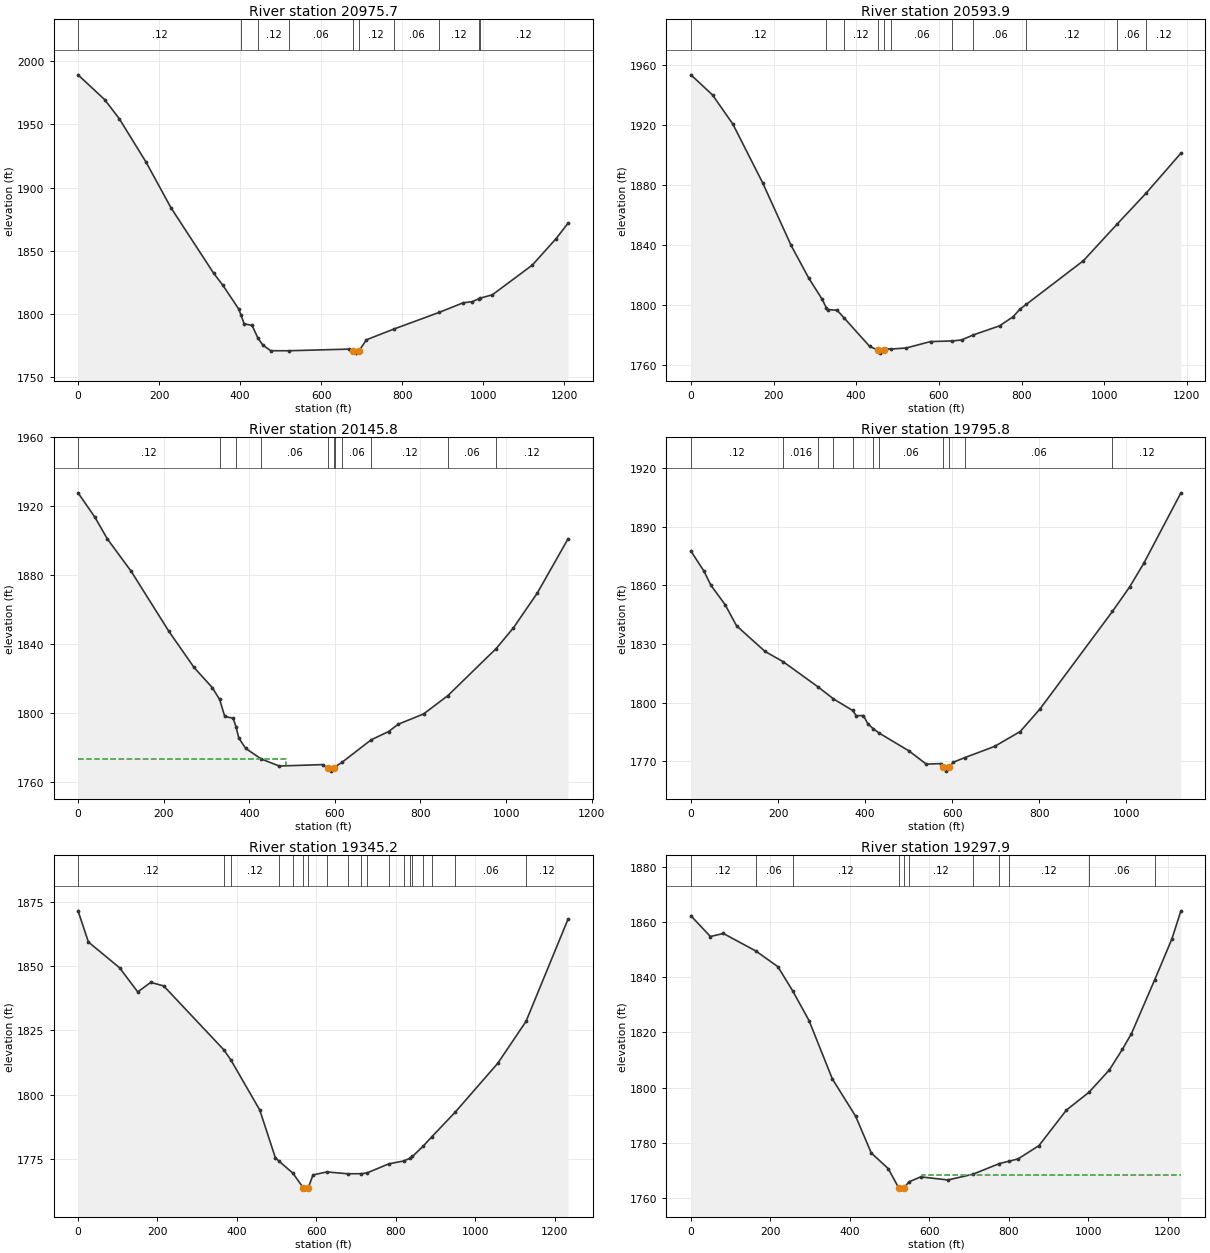
Type RM Length L Ch R = 1 ,20975.7 ,384.5,381.8,374.2
XS GIS Cut Line= 3
     2052289.355      224701.367     2051879.282      225148.507
     2051489.521      225608.054
#Sta/Elev= 30
       0 1989.09    65.6 1969.54   101.7 1954.45   167.2 1920.48   229.6 1883.92
   334.5 1832.44   357.5 1822.78   396.8 1803.93   402.31799.137   409.9 1792.42
   429.6 1791.09  443.891781.102   455.8 1775.63   475.5  1771.1  520.421771.075
   668.9 1772.38   678.6 1770.58   685.3  1769.2   693.6 1771.01   711.5 1779.72
  778.71 1788.13  891.671801.439   950.6 1808.98   973.5  1809.9   989.51812.282
  993.171812.695  1022.6  1815.3  1120.9  1838.7  1179.8 1859.68  1209.3 1871.88
#Mann= 10 ,-1 , 0
       0     .12       0   402.3    .016       0  443.89     .12       0
  520.42     .06       0   678.6    .045       0   693.6     .12       0
  778.71     .06       0  891.67     .12       0   989.5     .06       0
  993.17     .12       0
Bank Sta=678.6,693.6
XS Rating Curve= 0 ,0
Exp/Cntr=0.3,0.1

Type RM Length L Ch R = 1 ,20593.9 ,446.3,448.2,453.7
XS GIS Cut Line= 2
     2051905.094      224509.128     2051432.003      225596.367
#Sta/Elev= 30
       0 1953.29    52.4 1939.84   101.5 1920.46   173.6 1881.32   242.4 1839.61
     285 1817.85   317.7 1803.65  327.571798.053   330.8 1796.83   353.8 1796.36
  370.331791.354   432.4 1772.33     452 1769.82   458.6 1767.79  467.451769.708
   471.7 1770.79   483.7 1770.51   520.8 1771.21   579.8  1775.5  632.771775.899
   655.1  1776.6  683.571779.956   746.8 1785.97   779.6 1792.04   795.9 1797.05
  811.961800.391   949.9 1829.43 1031.921853.962 1101.921874.563  1185.7 1901.07
#Mann= 11 ,-1 , 0
       0     .12       0  327.57    .016       0  370.33     .12       0
     452    .045       0  467.45     .12       0   483.7     .06       0
  632.77    .016       0  683.57     .06       0  811.96     .12       0
 1031.92     .06       0 1101.92     .12       0
Bank Sta=452,467.45
XS Rating Curve= 0 ,0
Exp/Cntr=0.3,0.1

Type RM Length L Ch R = 1 ,20145.8 ,339.8,350,342.3
XS GIS Cut Line= 3
     2051576.457      224355.805     2051348.635      224904.684
     2050976.516      225310.464
#Sta/Elev= 30
       0 1927.85    39.2 1913.75    68.6 1901.05   124.1 1882.29   212.2 1847.44
     271 1826.45   313.5 1814.79  330.761807.868   342.8 1797.98   362.4 1796.98
  369.081791.985   375.5 1785.49   391.8 1779.42  428.271773.262   470.2 1769.21
   571.4 1770.03  583.221767.969     591 1766.24   597.6 1767.87  600.811768.761
  617.191771.448  684.821784.418   725.4 1789.22   748.3 1793.49   807.3 1799.45
  863.561809.994  976.991837.445    1017 1849.39  1072.8 1869.59  1144.8 1901.15
#Mann= 11 ,-1 , 0
       0     .12       0  330.76    .016       0  369.08     .12       0
  428.27     .06       0  583.22    .045       0   597.6     .06       0
  600.81     .12       0  617.19     .06       0  684.82     .12       0
  863.56     .06       0  976.99     .12       0
#XS Ineff= 2 , 0
          486.09 1773.39
Permanent Ineff=
       F       F
Bank Sta=583.22,597.6
XS Rating Curve= 0 ,0
Exp/Cntr=0.3,0.1

Type RM Length L Ch R = 1 ,19795.8 ,435.1,450.6,462.1
XS GIS Cut Line= 3
     2051393.082      224260.714     2051080.371      224756.527
     2050803.103      225218.636
#Sta/Elev= 30
       0 1877.57    29.5 1867.48    45.8 1860.12    78.6 1850.11   104.8 1839.31
   170.3 1826.16  211.251821.015  292.071808.016  327.311801.889  371.171795.982
   379.9 1793.25   396.2 1793.37   406.1 1789.17  418.111786.725  432.081784.395
     501 1775.21   540.3  1768.5   573.1 1768.75   578.7 1767.23   586.2  1764.9
   593.7 1767.17   602.5 1769.46  629.471771.874   697.2 1777.55     756 1785.16
   801.8 1796.81  967.891846.691  1007.5 1859.25  1040.2 1871.46  1125.1  1907.4
#Mann= 11 ,-1 , 0
       0     .12       0  211.25    .016       0  292.07     .06       0
  327.31     .12       0  371.17    .016       0  418.11     .12       0
  432.08     .06       0   578.7    .045       0   593.7     .12       0
  629.47     .06       0  967.89     .12       0
Bank Sta=578.7,593.7
XS Rating Curve= 0 ,0
Exp/Cntr=0.3,0.1

Type RM Length L Ch R = 1 ,19345.2 ,47.6,47.4,47.8
XS GIS Cut Line= 3
     2051373.952      224231.893     2050764.143      224447.821
     2050587.928      225007.356
#Sta/Elev= 30
       0 1871.47    26.1 1859.33   104.6 1849.31   150.3 1839.93     183 1843.63
   215.6 1842.25  367.421817.316  384.92 1813.39   457.4 1793.99   496.6 1775.47
  506.511773.974  540.651769.443   566.6  1763.8   571.8 1763.19  579.941763.818
   591.4  1768.7   626.21769.893  679.041769.162  712.731769.196  727.731769.507
  782.12 1773.02  820.051774.155  834.571775.119  841.881775.917  868.071779.797
  889.911783.452  949.521793.153  1056.6 1812.16 1127.641828.438  1233.5 1868.25
#Mann= 19 ,-1 , 0
       0     .12       0  367.42     .06       0  384.92     .12       0
  506.51    .016       0  540.65     .12       0   566.6    .045       0
  579.94     .12       0   626.2    .016       0  679.04     .06       0
  712.73     .12       0  727.73     .06       0  782.12     .12       0
  820.05     .06       0  834.57     .08       0  841.88     .12       0
  868.07     .06       0  889.91     .12       0  949.52     .06       0
 1127.64     .12       0
Bank Sta=566.6,579.94
XS Rating Curve= 0 ,0
Exp/Cntr=0.3,0.1

Type RM Length L Ch R = 1 ,19297.9 ,394.7,386.4,370.9
XS GIS Cut Line= 3
     2051311.018      224204.766     2050701.209      224420.695
     2050524.994      224980.229
#Sta/Elev= 30
       0  1862.2      49 1854.69    81.7 1855.79  163.231849.462   218.9 1843.77
  256.291834.976   297.3 1824.27   356.1 1803.11   414.9 1789.56   454.1  1776.3
   496.6 1770.68   522.8 1763.75   529.3 1763.22   535.8 1763.67  549.191765.868
   578.3 1767.66   646.9 1766.54  709.751768.609  776.781772.491  801.471773.354
   823.9 1774.19   876.3    1779   945.1 1791.82 1002.191798.313  1053.3 1806.38
  1086.1 1813.83    1109 1819.54  1167.71839.091  1210.6 1853.75  1233.5 1863.99
#Mann= 11 ,-1 , 0
       0     .12       0  163.23     .06       0  256.29     .12       0
   522.8    .045       0   535.8    .016       0  549.19     .12       0
  709.75    .016       0  776.78     .06       0  801.47     .12       0
 1002.19     .06       0  1167.7     .12       0
#XS Ineff= 2 , 0
                          580.78         1768.25
Permanent Ineff=
       F       F
Bank Sta=522.8,535.8
XS Rating Curve= 0 ,0
Exp/Cntr=0.3,0.1

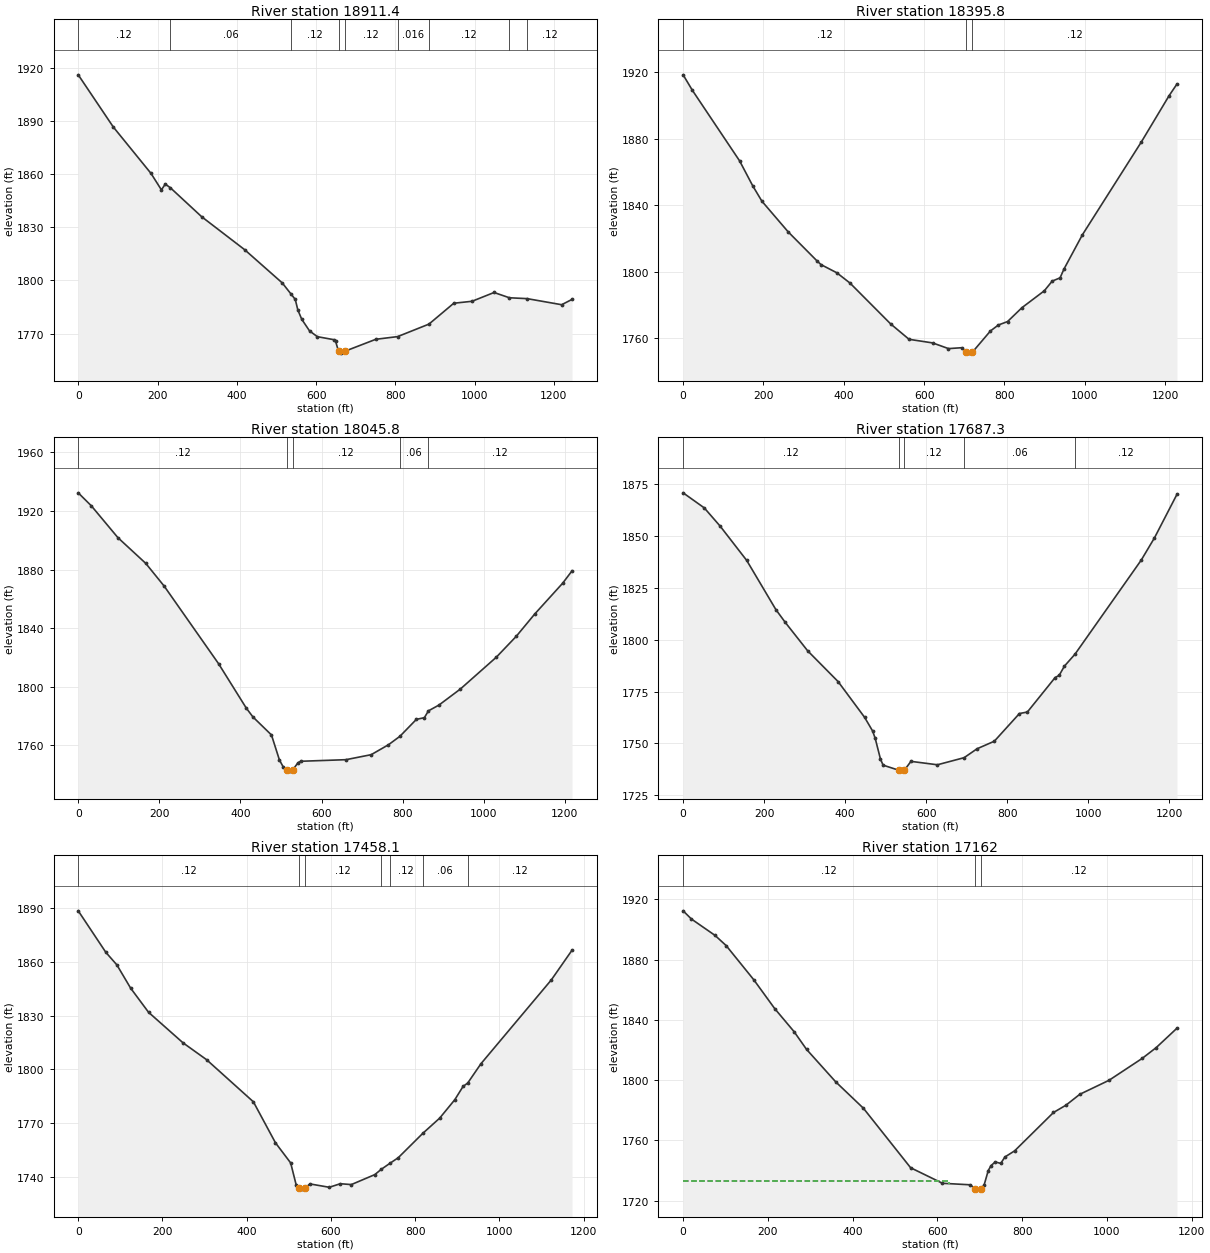
Type RM Length L Ch R = 1 ,18911.4 ,500.1,515.7,535.6
XS GIS Cut Line= 2
     2050847.259      223772.908     2050198.388      224836.276
#Sta/Elev= 30
       0 1916.03    88.5 1886.56   183.6 1860.37   209.8 1851.09   219.6 1854.35
  232.681852.226   311.4 1835.92   419.6 1817.35   514.7 1798.55  536.991792.217
   547.5 1789.24     554 1783.27   563.8 1778.05   583.5 1771.47   603.2 1768.21
   645.8 1766.47   649.1 1765.74  656.641759.897   662.2 1758.92     672 1759.93
   750.7 1766.73  805.751768.249   884.71775.297   947.4 1787.09   993.3 1788.18
    1049 1793.15 1087.671790.174 1132.461789.681  1219.5 1786.25  1245.7 1789.26
#Mann= 9 ,-1 , 0
       0     .12       0  232.68     .06       0  536.99     .12       0
  656.64    .045       0     672     .12       0  805.75    .016       0
   884.7     .12       0 1087.67     .06       0 1132.46     .12       0
Bank Sta=656.64,672
XS Rating Curve= 0 ,0
Exp/Cntr=0.3,0.1

Type RM Length L Ch R = 1 ,18395.8 ,341.9,350,342.8
XS GIS Cut Line= 3
     2050822.468      223741.565     2050171.198      224031.841
     2049657.112      224082.474
#Sta/Elev= 30
       0 1918.42    22.9 1909.16   140.6 1866.68   173.4 1851.62   196.2  1842.4
   261.7 1823.93   333.6 1806.44   343.4 1804.26   382.7 1799.35   415.4 1793.19
   516.8 1768.58   562.6 1759.33   621.4 1757.16   660.7 1753.74   693.4 1754.27
   705.5 1751.71     713 1751.02   720.5 1751.65   765.3 1764.37     785 1767.94
   807.8    1770   843.8 1778.38   899.4 1788.52     919 1794.34   938.6  1796.3
   948.4 1801.63   994.2  1822.2  1141.3 1878.16    1210 1905.85  1229.6 1912.86
#Mann= 3 ,-1 , 0
       0     .12       0   705.5    .045       0   720.5     .12       0
Bank Sta=705.5,720.5
XS Rating Curve= 0 ,0
Exp/Cntr=0.3,0.1

Type RM Length L Ch R = 1 ,18045.8 ,373.9,358.5,350.8
XS GIS Cut Line= 3
     2050800.993      223655.583     2050285.011      223736.931
     2049636.131       223987.28
#Sta/Elev= 30
       0 1932.38    32.6 1923.42    97.9 1901.75   166.5 1884.22   212.2 1868.59
   346.1 1815.69   414.6 1785.31   430.9 1779.31   476.6 1767.01   496.2 1749.95
     506 1744.97   514.9 1743.01   522.4 1742.32   528.9 1743.16     542 1748.03
   548.6 1749.05   660.1 1750.13   722.5 1753.55   765.1 1760.32  793.321766.088
     834 1777.67   853.7 1778.82  863.721783.489   889.8 1787.46   942.3 1798.35
  1030.9 1820.06  1080.1 1834.31    1126 1849.66  1194.9  1870.7  1217.9 1879.12
#Mann= 5 ,-1 , 0
       0     .12       0   514.9    .045       0   528.9     .12       0
  793.32     .06       0  863.72     .12       0
Bank Sta=514.9,528.9
XS Rating Curve= 0 ,0
Exp/Cntr=0.3,0.1

Type RM Length L Ch R = 1 ,17687.3 ,230.1,229.2,221.7
XS GIS Cut Line= 3
     2050344.931      222991.041     2050121.814      223471.456
     2049593.037      223913.647
#Sta/Elev= 30
       0 1870.85    52.3 1863.57    91.6 1854.74     157 1838.25   228.9 1814.57
   251.8 1808.46   307.4 1794.68   382.6 1779.83     448  1762.6   467.6 1756.06
   474.1 1752.52   487.2 1742.43   493.7 1739.54     533 1737.05   542.8 1736.66
     546 1737.05   562.4 1741.37   627.7 1739.72  693.661743.144   725.7 1747.45
   768.2 1751.08   830.2 1764.43   849.8 1765.16   918.4  1781.8   928.2  1782.8
   941.3  1787.3  967.171793.005  1130.8 1838.39  1163.5 1849.12    1219  1870.1
#Mann= 5 ,-1 , 0
       0     .12       0     533    .045       0     546     .12       0
  693.66     .06       0  967.17     .12       0
Bank Sta=533,546
XS Rating Curve= 0 ,0
Exp/Cntr=0.3,0.1

Type RM Length L Ch R = 1 ,17458.1 ,289.2,296.1,301.4
XS GIS Cut Line= 2
      2050233.11      222907.023     2049577.728      223879.245
#Sta/Elev= 30
       0 1888.41    65.5  1865.3    91.7 1858.29   124.4 1845.33     167 1831.86
   248.9 1814.82   304.6 1805.47   415.9 1781.96   468.3 1759.13   504.4 1747.91
   517.5 1735.64     524 1733.99   530.6  1733.3  538.461733.971   550.2  1736.2
   596.1 1734.33   622.3 1736.31   648.5 1735.84   704.2 1741.39  719.55 1744.35
  740.011747.679   759.8  1750.8   818.21764.407   858.1 1772.85   894.1 1783.13
   913.8 1790.56  924.69  1792.4   956.3 1803.22  1123.4 1849.94  1172.5 1866.48
#Mann= 7 ,-1 , 0
       0     .12       0     524    .045       0  538.46     .12       0
  719.55     .06       0  740.01     .12       0   818.2     .06       0
  924.69     .12       0
Bank Sta=524,538.46
XS Rating Curve= 0 ,0
Exp/Cntr=0.3,0.1

Type RM Length L Ch R = 1 ,17162   ,198.4,217.4,236
XS GIS Cut Line= 2
     2050191.877       222870.13     2049306.461      223627.509
#Sta/Elev= 30
       0  1912.3    19.6 1906.86    75.3    1896   101.5 1889.25   166.9 1866.49
     216 1847.46   261.8 1832.13   291.3 1820.34     360 1798.83   425.5 1781.27
   536.8 1741.82     612 1731.51   677.5  1730.5   688.5 1727.96   697.1 1727.63
   703.5 1727.97   710.2 1730.35     720 1739.96   726.6 1743.25   736.4 1745.66
   749.5 1744.71   759.3 1748.96   782.2 1753.02   873.9 1778.48   903.3 1783.32
     936 1790.55  1004.8 1799.82  1083.3 1814.39  1116.1 1821.49  1165.2 1834.39
#Mann= 3 ,-1 , 0
       0     .12       0   688.5    .045       0   703.5     .12       0
#XS Ineff= 2 , 0
          628.13 1733.35
Permanent Ineff=
       F       F
Bank Sta=688.5,703.5
XS Rating Curve= 0 ,0
Exp/Cntr=0.3,0.1

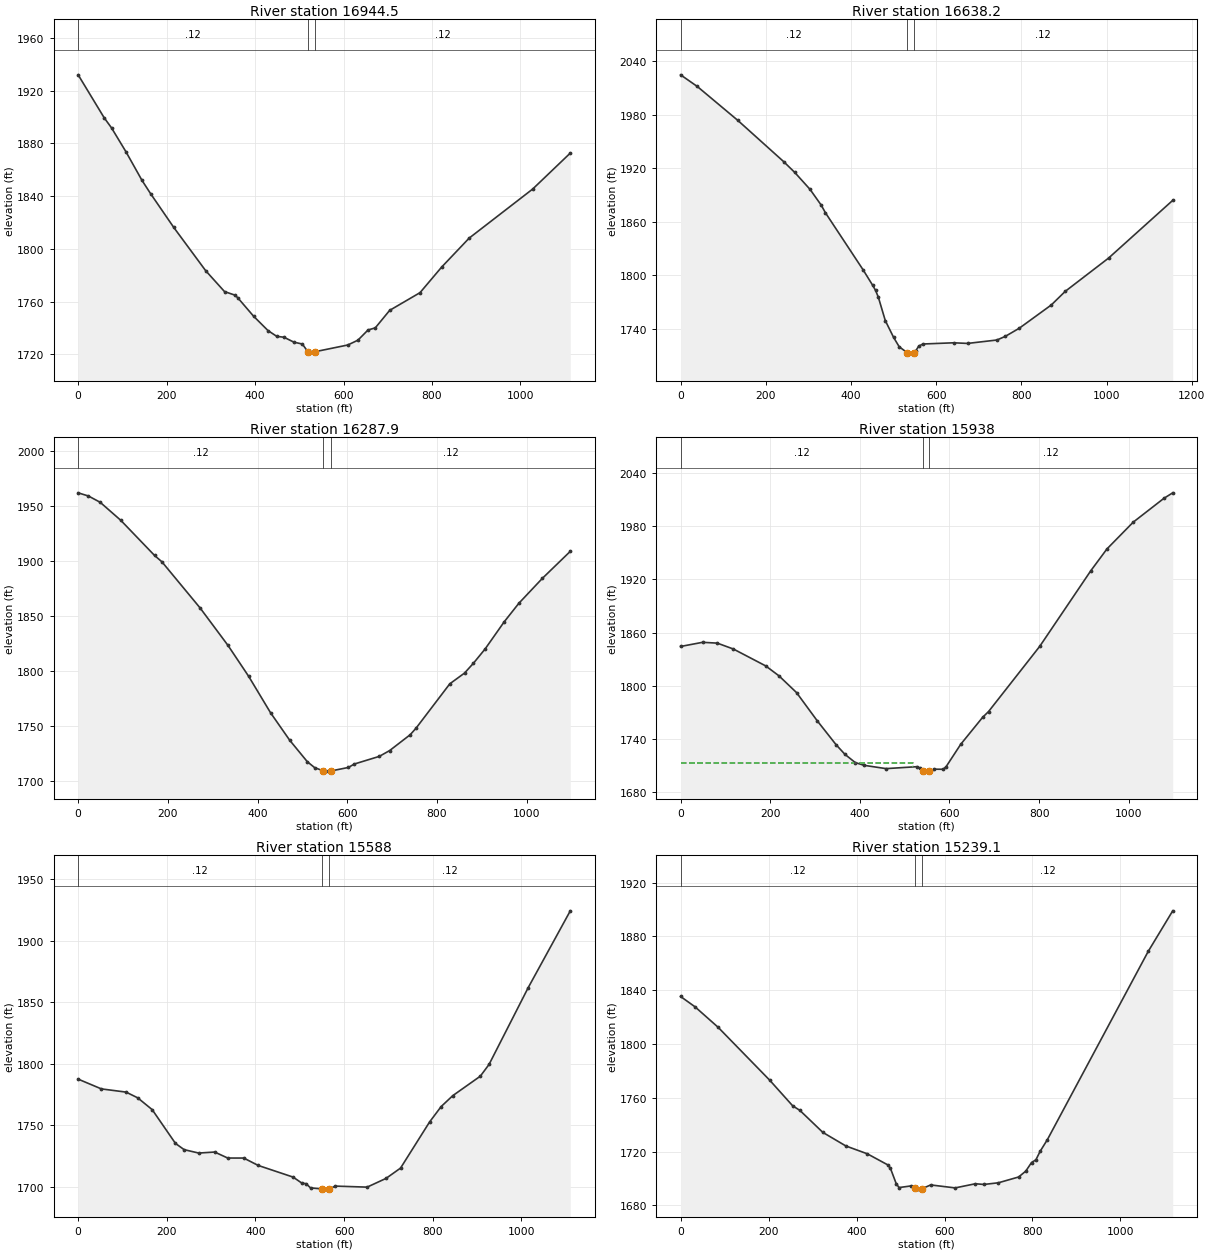
Type RM Length L Ch R = 1 ,16944.5 ,330.5,306.3,291.5
XS GIS Cut Line= 4
     2050029.117      222785.495     2049712.277      223126.207
     2049575.558      223108.846      2049135.02      223364.922
#Sta/Elev= 30
       0  1931.9      59 1899.27    75.4 1891.73   108.1 1873.59   144.2    1852
   163.8 1841.84   216.2 1816.24   288.3 1783.49   330.9 1767.65   353.9 1765.03
   360.4 1763.14   396.5 1749.03   429.2 1738.11   448.9 1733.75   465.3 1733.06
   487.7 1729.34   506.9  1727.9   519.8 1721.86     523 1721.02   535.8 1722.11
   609.6 1727.18   632.5 1730.84   655.3 1738.55   671.7 1740.15   704.3 1753.44
   772.9 1766.85   821.9 1786.27     884 1808.18  1027.7 1845.39  1112.6 1872.61
#Mann= 3 ,-1 , 0
       0     .12       0   519.8    .045       0   535.8     .12       0
Bank Sta=519.8,535.8
XS Rating Curve= 0 ,0
Exp/Cntr=0.3,0.1

Type RM Length L Ch R = 1 ,16638.2 ,348.4,350.3,340.3
XS GIS Cut Line= 3
     2049913.311      222418.265     2049604.954      222860.909
     2049063.999      223155.421
#Sta/Elev= 30
       0  2024.6    39.2 2011.57     134 1973.73   241.9 1927.44   268.1 1915.27
   304.1 1896.22   330.2 1878.64     340 1870.18   428.3 1806.37   451.2 1788.72
   457.7 1783.24   464.3 1775.56   480.6 1749.38   500.2 1730.49   513.3 1720.01
     532 1713.47   539.5 1712.92     547 1713.43   552.6 1715.81   559.1 1720.78
     569 1723.14     641 1724.49   673.8 1723.79   742.6 1727.61   762.2 1731.65
     795 1740.75   870.4 1766.89   903.1 1782.12  1004.7 1819.32  1155.4 1884.01
#Mann= 3 ,-1 , 0
       0     .12       0     532    .045       0     547     .12       0
Bank Sta=532,547
XS Rating Curve= 0 ,0
Exp/Cntr=0.3,0.1

Type RM Length L Ch R = 1 ,16287.9 ,345.7,350,354.7
XS GIS Cut Line= 3
     2049662.061      222220.159     2049324.513      222654.669
     2048990.232      223087.686
#Sta/Elev= 30
       0 1962.08    22.9 1959.19    49.1 1953.49      95 1937.11   170.3 1905.17
   186.7  1899.4   271.8 1857.48   334.1 1823.36   379.9 1795.44     429 1762.14
   471.6 1737.23   510.9 1717.68   527.3 1712.28   546.9 1709.31   556.8 1709.12
   563.3 1709.24   602.6 1712.47   615.7 1715.58   671.4 1722.53   694.4 1727.79
   740.2 1742.18   753.3 1748.16   828.6  1788.5   861.4 1798.25   881.1 1807.12
   907.3 1820.16   949.8 1844.82   982.6 1861.72    1035 1884.37  1097.2  1908.9
#Mann= 3 ,-1 , 0
       0     .12       0   546.9    .045       0   563.3     .12       0
Bank Sta=546.9,563.3
XS Rating Curve= 0 ,0
Exp/Cntr=0.3,0.1

Type RM Length L Ch R = 1 ,15938   ,339.8,349.9,353.9
XS GIS Cut Line= 3
     2049487.027      222041.679     2049083.591      222415.767
     2048652.375      222753.989
#Sta/Elev= 30
       0 1844.24    49.1 1848.94    81.9 1848.02   117.9 1841.35   189.9  1822.3
   219.4 1811.12   258.7 1792.16   304.6 1760.47   347.1 1733.15   366.8 1722.31
   389.7 1713.05   409.4 1709.91   458.5 1706.17   527.3 1708.36   533.8 1707.04
   540.4 1703.69   546.9 1703.34   553.4 1703.62   566.5 1705.55   586.1 1705.42
   592.6 1708.44   625.2 1733.72   674.1  1764.2   687.2 1770.65   801.4 1844.36
   915.5 1929.92   951.4 1954.46  1010.1 1984.77  1078.6 2011.71  1098.2 2017.91
#Mann= 3 ,-1 , 0
       0     .12       0   540.4    .045       0   553.4     .12       0
#XS Ineff= 2 , 0
          518.89  1712.6
Permanent Ineff=
       F       F
Bank Sta=540.4,553.4
XS Rating Curve= 0 ,0
Exp/Cntr=0.3,0.1

Type RM Length L Ch R = 1 ,15588   ,357.4,348.9,338
XS GIS Cut Line= 3
     2049432.816      221953.737      2048895.65      222124.444
      2048420.88      222395.704
#Sta/Elev= 30
       0  1787.6    52.4 1779.66   108.1 1777.06   134.4  1772.4   167.1  1762.8
   219.6 1735.38   239.2 1730.31     272 1727.56     308 1728.38   337.5 1723.51
   373.6  1723.5   406.3 1717.49     485 1708.03   504.6 1703.18   514.5 1702.65
   524.3 1699.24   550.5 1698.46   560.4 1698.26   566.9 1698.39     580 1700.72
     652 1699.88   694.6 1706.96   727.4 1715.35   792.8 1752.74     819 1765.31
   845.2 1774.17   907.4 1789.99   927.1 1799.54  1015.5 1861.95  1110.4 1924.28
#Mann= 3 ,-1 , 0
       0     .12       0   550.5    .045       0   566.9     .12       0
Bank Sta=550.5,566.9
XS Rating Curve= 0 ,0
Exp/Cntr=0.3,0.1

Type RM Length L Ch R = 1 ,15239.1 ,359.2,350,348.5
XS GIS Cut Line= 3
     2049118.104      221507.757     2048710.948      221866.039
     2048360.161      222323.497
#Sta/Elev= 30
       0 1835.32    32.7 1827.67      85 1812.53   202.6  1773.1   254.8 1754.06
   271.2 1750.65   323.4  1734.3   375.7 1724.21   424.7 1718.35   470.5 1710.24
     477 1707.68   490.1 1696.28   496.6 1693.28   522.8 1694.46   532.6 1692.63
   539.1 1692.12   548.9 1692.46   568.6 1695.24   624.2 1693.03   670.1 1696.11
   689.7  1695.6   722.5 1696.84   768.4 1701.13   784.7 1705.48   797.8 1711.87
   807.7  1713.9   817.5 1720.28   833.9 1728.93  1063.1 1868.84  1118.8 1898.98
#Mann= 3 ,-1 , 0
       0     .12       0   532.6    .045       0   548.9     .12       0
Bank Sta=532.6,548.9
XS Rating Curve= 0 ,0
Exp/Cntr=0.3,0.1

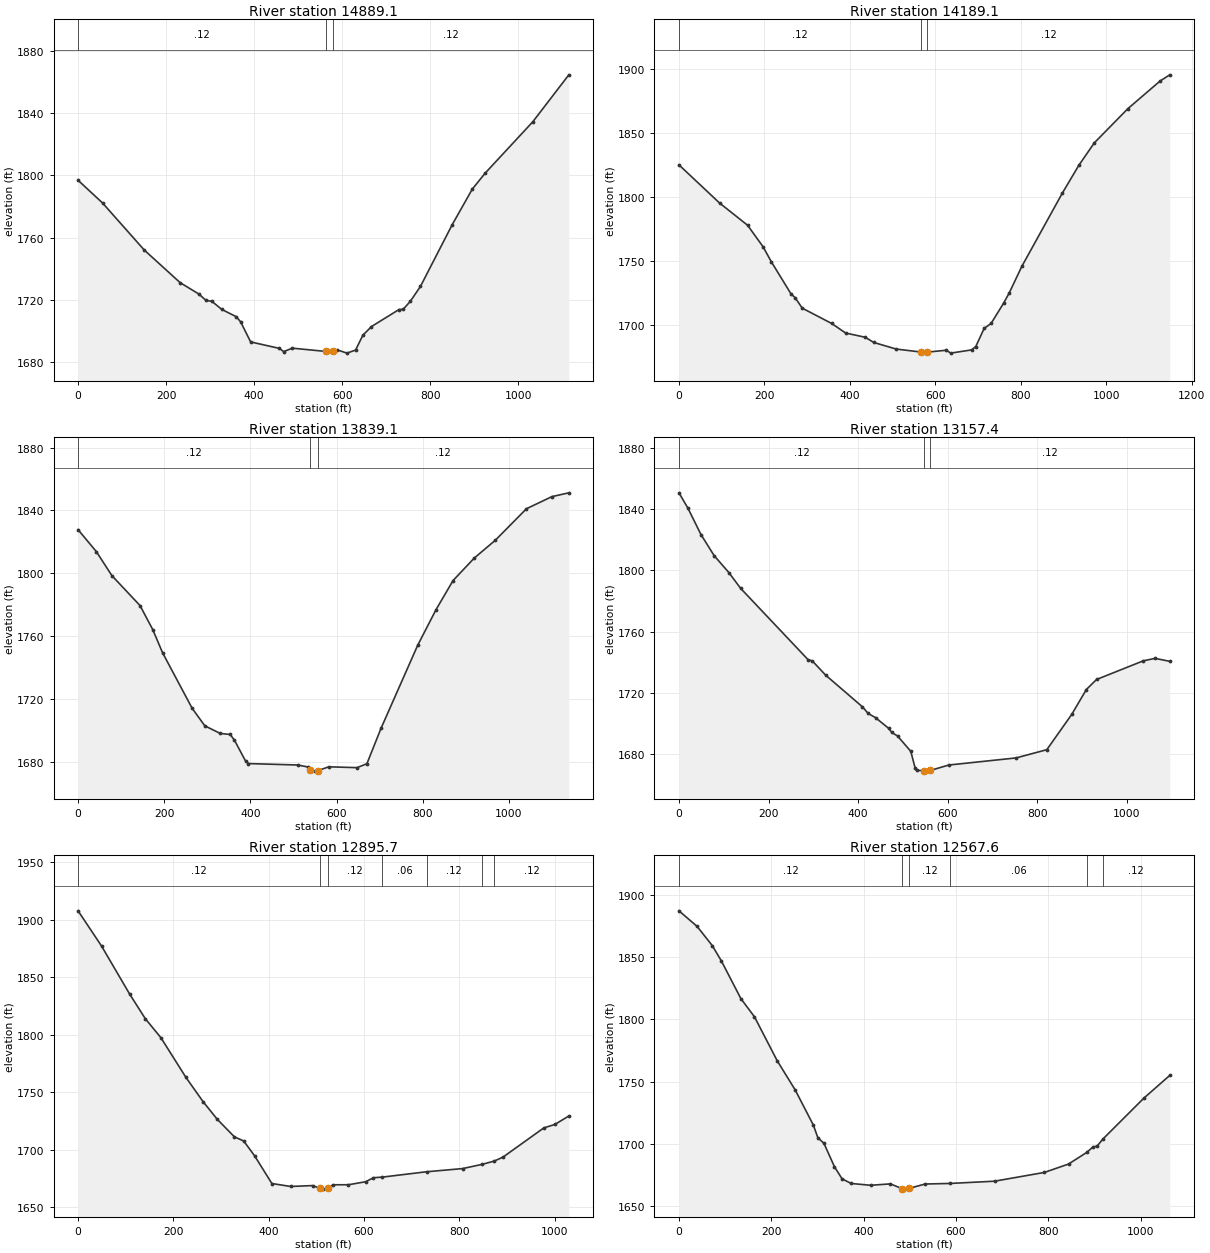
Type RM Length L Ch R = 1 ,14889.1 ,693.9,700,698.7
XS GIS Cut Line= 3
     2048641.112        221223.9     2048408.657      221746.419
     2048108.788      222199.749
#Sta/Elev= 30
       0 1796.75    55.6  1782.2   150.3 1752.01     232 1731.02   274.5 1723.73
   290.8 1719.63   303.9 1719.08   326.8 1713.83   359.5 1709.18   369.3 1705.96
   392.2 1692.99   457.5 1688.84   467.3 1686.76   486.9 1688.98   564.4 1686.84
   579.4 1686.89   588.3 1687.94   611.2 1685.79   630.8 1687.78   647.2 1697.25
   666.8 1702.84   729.1 1713.73   738.9 1713.93   755.2 1719.06   778.2 1728.65
   850.2 1768.19     896  1791.1   925.5 1801.42  1033.6 1834.35  1115.4 1864.46
#Mann= 3 ,-1 , 0
       0     .12       0   564.4    .045       0   579.4     .12       0
Bank Sta=564.4,579.4
XS Rating Curve= 0 ,0
Exp/Cntr=0.3,0.1

Type RM Length L Ch R = 1 ,14189.1 ,341.3,350,356.3
XS GIS Cut Line= 3
     2048105.657      220940.393     2047968.229      221497.459
     2047840.915       222057.88
#Sta/Elev= 30
       0  1825.4    95.1 1795.57   160.6 1778.24   196.7 1761.51   216.4 1749.58
   262.3 1724.61   272.1 1721.59   288.5  1713.5   357.4 1701.54   390.2 1694.05
   436.1 1690.78   455.7 1686.74   508.2 1681.58   566.3 1679.25   581.3 1679.17
     626 1680.66   635.8 1678.39   684.8 1680.91   694.6 1683.53   714.2 1697.66
   730.5 1701.59   759.9 1717.48     773 1725.46   802.3 1746.08     897 1803.23
   936.2 1825.26   972.1 1842.61  1050.5 1869.26  1125.6 1890.77  1148.5  1895.7
#Mann= 3 ,-1 , 0
       0     .12       0   566.3    .045       0   581.3     .12       0
Bank Sta=566.3,581.3
XS Rating Curve= 0 ,0
Exp/Cntr=0.3,0.1

Type RM Length L Ch R = 1 ,13839.1 ,682.4,681.7,681.4
XS GIS Cut Line= 3
     2048031.424       220906.09     2047733.579      221363.738
     2047452.711      221886.405
#Sta/Elev= 30
       0 1827.77    42.5  1813.8    78.5 1798.56   143.9  1779.5   173.3 1764.29
   196.2  1749.5   264.8 1714.23   294.3 1703.05   330.2 1698.21   353.1 1697.56
   362.9 1694.01   389.1 1680.54   395.6 1679.06   510.1 1678.15     533 1676.94
   539.5 1674.77   549.3 1674.26   555.9 1674.52   582.1    1677   647.7 1676.47
   670.6 1678.97   703.4  1701.5   788.6 1754.34   831.2 1776.99   870.6 1795.44
   919.8 1809.71   968.9  1821.1    1041 1841.08    1100 1848.78  1139.4  1851.2
#Mann= 3 ,-1 , 0
       0     .12       0   539.5    .045       0   555.9     .12       0
Bank Sta=539.5,555.9
XS Rating Curve= 0 ,0
Exp/Cntr=0.3,0.1

Type RM Length L Ch R = 1 ,13157.4 ,263.2,261.7,259.2
XS GIS Cut Line= 3
     2047537.387      220594.473      2047298.86      221086.929
     2047023.515      221561.801
#Sta/Elev= 30
       0 1850.72    19.7 1840.87    49.2 1823.42    78.6 1809.67   111.4 1798.62
   137.6 1788.34   288.3 1741.71   298.2 1740.78   327.6 1731.58   409.6 1710.92
   422.7 1706.52   439.1 1703.77   468.5 1696.78   475.1 1694.18   488.2 1691.81
   517.7 1681.82   527.5 1670.89   530.8 1669.27   547.2 1669.26     557 1668.85
  561.211669.285   602.7 1672.84     753 1677.48   821.6 1682.86   877.2 1705.89
   909.9 1722.19   932.7 1728.74  1037.3 1740.95  1063.4 1742.53  1096.1 1740.61
#Mann= 3 ,-1 , 0
       0     .12       0   547.2    .045       0  561.21     .12       0
Bank Sta=547.2,561.21
XS Rating Curve= 0 ,0
Exp/Cntr=0.3,0.1

Type RM Length L Ch R = 1 ,12895.7 ,334.5,328.2,318.9
XS GIS Cut Line= 2
     2047273.041      220509.019     2046852.034      221448.689
#Sta/Elev= 30
       0 1907.57    49.2 1877.02   108.2 1835.28     141 1813.96   173.8 1797.39
   226.3 1762.93   262.3 1741.86   291.8 1726.68   327.9 1711.36   347.6 1707.68
   370.6 1694.72   406.6 1670.79     446 1668.23   491.9    1669   508.3 1666.51
   514.8 1665.92   524.7 1666.62   534.5 1669.68   567.3 1669.73   603.4 1672.33
   619.8 1675.83  638.281676.351  731.11    1681   806.7 1683.75  847.851687.438
  873.451690.302     892 1693.84   977.2 1719.08  1000.2 1722.05  1029.7 1729.41
#Mann= 7 ,-1 , 0
       0     .12       0   508.3    .045       0   524.7     .12       0
  638.28     .06       0  731.11     .12       0  847.85    .016       0
  873.45     .12       0
Bank Sta=508.3,524.7
XS Rating Curve= 0 ,0
Exp/Cntr=0.3,0.1

Type RM Length L Ch R = 1 ,12567.6 ,405.6,404.1,393.2
XS GIS Cut Line= 2
     2046867.225      220346.259     2046752.207      221403.117
#Sta/Elev= 30
       0 1887.05    39.2 1874.59      72 1859.23    91.6 1847.04   134.1 1816.65
   163.6 1802.01   212.6 1766.92   251.9 1743.28   291.1  1715.2   300.9 1704.99
     314 1700.58   336.9 1681.72   353.3 1672.08   372.9 1668.34   415.4 1666.88
     458 1668.02   484.1 1664.07   490.7  1663.8  498.091664.339   533.2  1667.9
  586.971668.351   683.6 1670.16   791.6  1677.2   843.9 1683.92  883.441693.265
   896.3 1697.44   906.1 1698.42  917.761703.771  1007.5 1736.93  1063.1    1755
#Mann= 6 ,-1 , 0
       0     .12       0   484.1    .045       0  498.09     .12       0
  586.97     .06       0  883.44    .016       0  917.76     .12       0
Bank Sta=484.1,498.09
XS Rating Curve= 0 ,0
Exp/Cntr=0.3,0.1