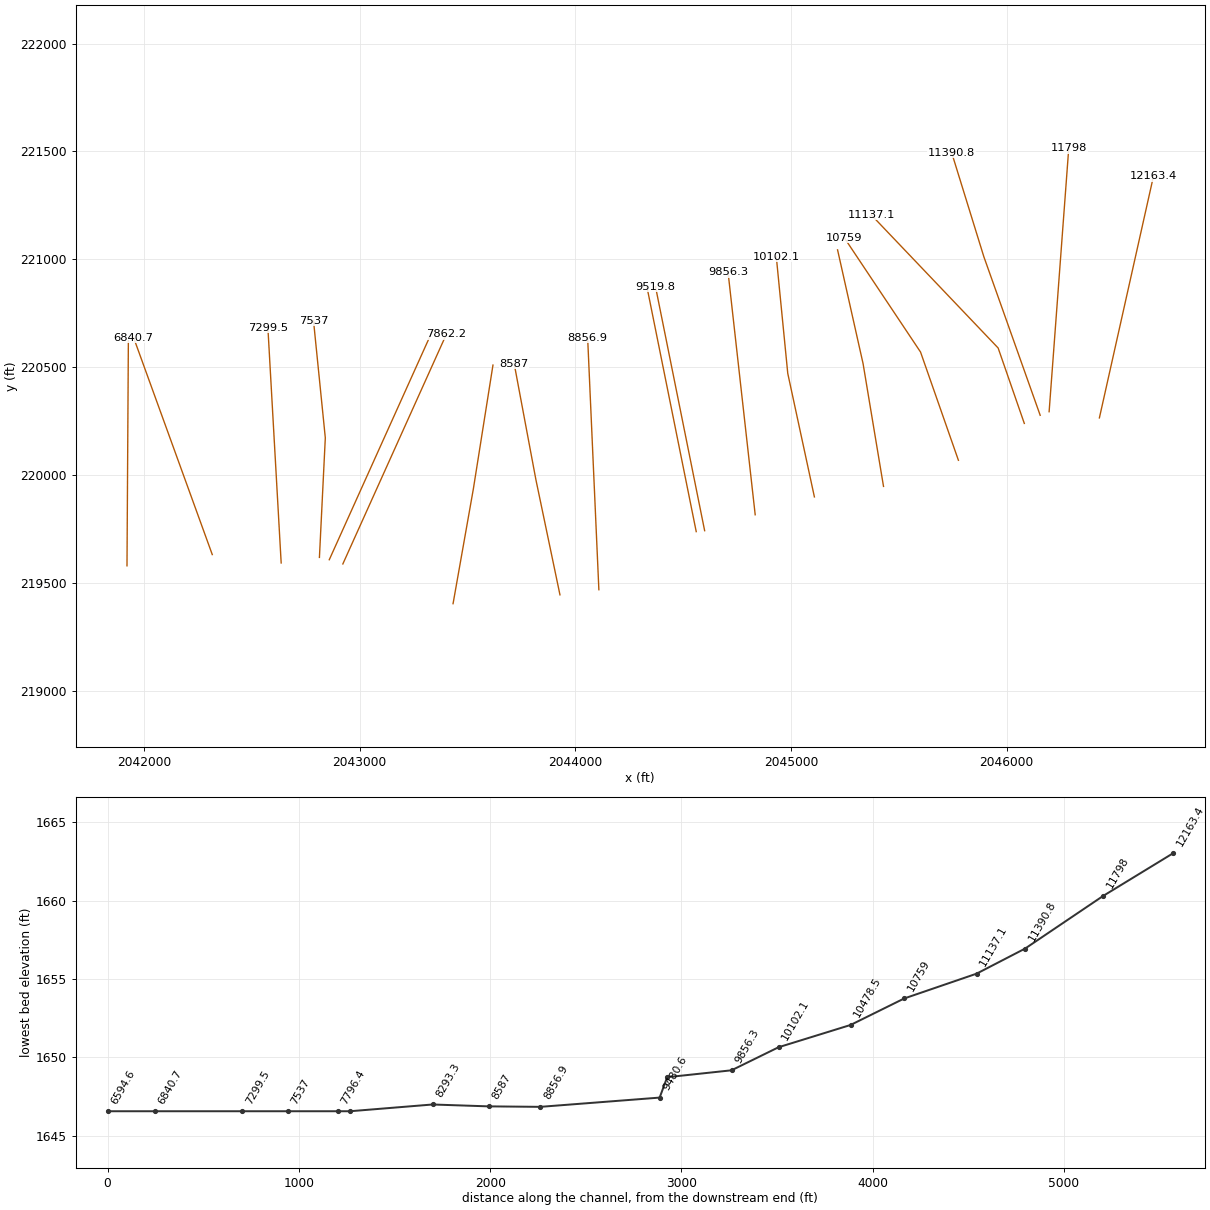
HEC-RAS study STONYCK.prj: STONYCK

--- STONYCK.g01 (geometry) --- (continued)

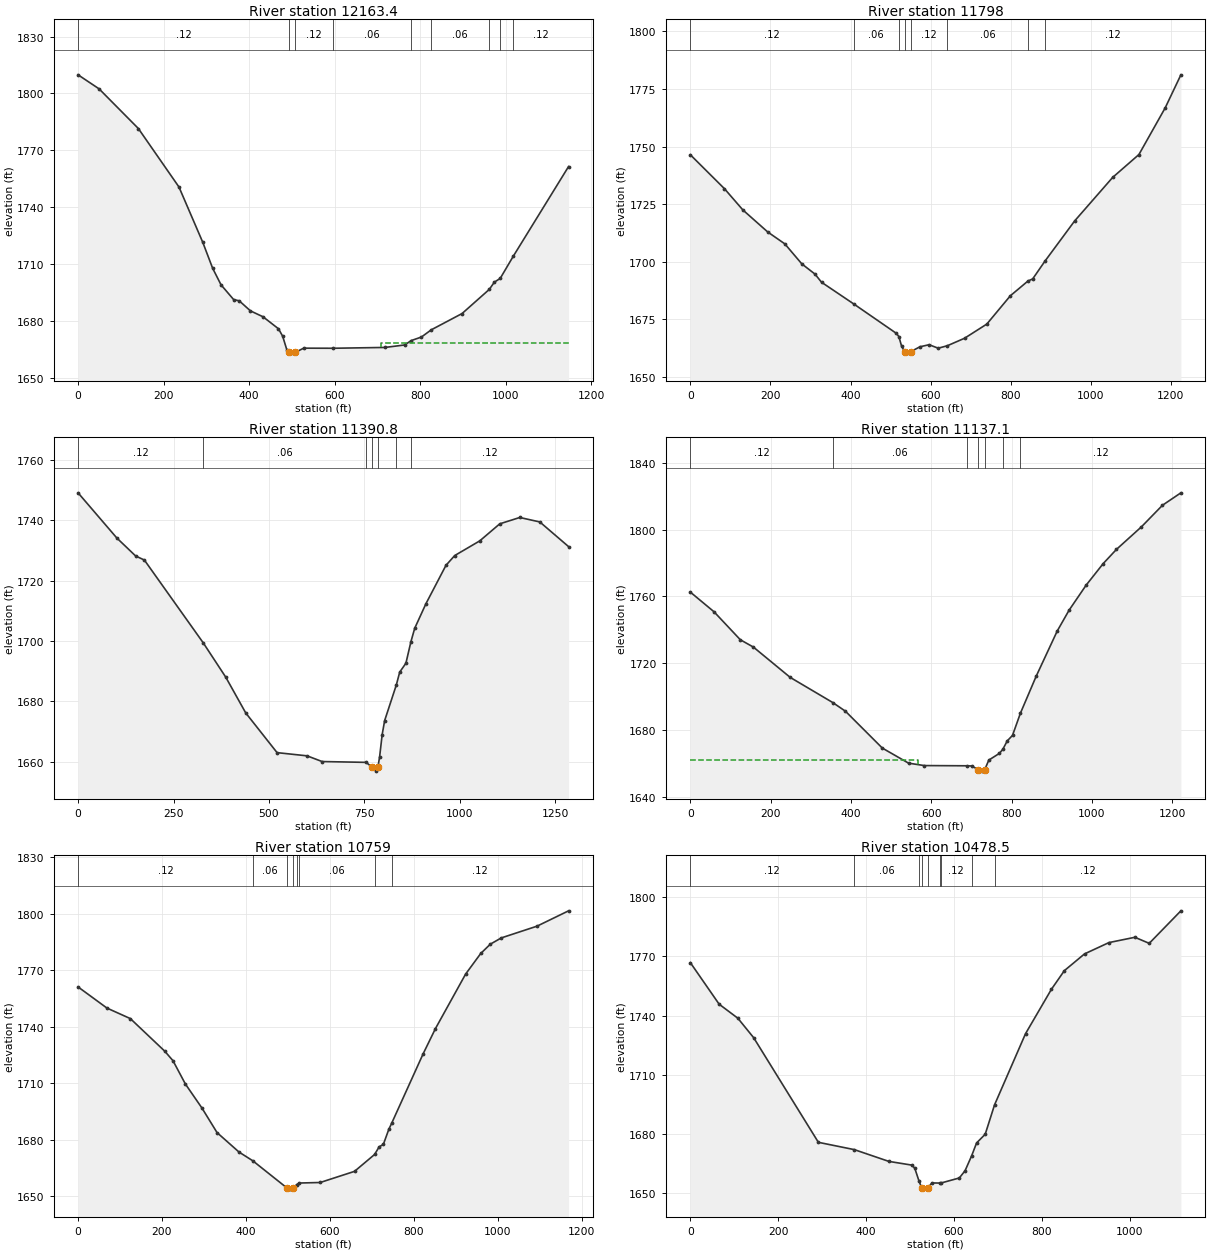
Type RM Length L Ch R = 1 ,12163.4 ,362.3,365.4,367.5
XS GIS Cut Line= 2
     2046429.756      220265.528     2046680.464      221385.134
#Sta/Elev= 30
       0 1809.84    49.2 1802.43     141 1781.52     236 1750.66   291.8 1721.41
   314.7 1707.83   334.4 1699.04   363.9 1691.26     377  1690.6   403.2  1685.3
   432.7 1682.18   468.8 1675.85   478.6 1671.91   488.4 1664.68  493.321663.419
   498.3 1663.01   508.1 1663.42   527.8 1665.63  596.831665.581   717.9 1666.01
   763.8 1667.31  779.331669.646   803.1  1671.5  826.141675.306   898.2  1683.9
  961.831696.629   973.6 1700.43  987.421702.446 1017.691714.029  1147.3 1761.46
#Mann= 9 ,-1 , 0
       0     .12       0  493.32    .045       0   508.1     .12       0
  596.83     .06       0  779.33     .12       0  826.14     .06       0
  961.83    .016       0  987.42     .06       0 1017.69     .12       0
#XS Ineff= 2 , 0
                          709.27         1668.58
Permanent Ineff=
       F       F
Bank Sta=493.32,508.1
XS Rating Curve= 0 ,0
Exp/Cntr=0.3,0.1

Type RM Length L Ch R = 1 ,11798   ,396.8,407.2,414.2
XS GIS Cut Line= 2
     2046196.652      220294.176     2046287.798      221515.964
#Sta/Elev= 30
       0 1746.42    85.2 1731.68     131 1722.49   193.3 1712.89   235.9 1707.74
   278.4 1699.04   311.2 1694.62   327.6 1691.07  407.911681.668   514.3  1668.9
   520.8 1667.48   527.4  1663.4   534.9 1660.96   540.5 1660.29   550.4 1660.92
   573.3 1663.04   596.2 1663.94   619.1 1662.43  641.951663.507   684.7 1666.74
   740.4  1672.9   799.3 1685.21  843.141691.592     855 1692.52   885.91700.299
   959.8 1717.69  1054.8  1736.6  1120.4 1746.54  1185.9 1766.77  1225.2 1781.15
#Mann= 8 ,-1 , 0
       0     .12       0  407.91     .06       0   520.8     .12       0
   534.9    .045       0   550.4     .12       0  641.95     .06       0
  843.14    .016       0   885.9     .12       0
Bank Sta=534.9,550.4
XS Rating Curve= 0 ,0
Exp/Cntr=0.3,0.1

Type RM Length L Ch R = 1 ,11390.8 ,244,253.7,263.9
XS GIS Cut Line= 3
     2046155.196      220277.728      2045893.86      221012.744
     2045744.671      221494.811
#Sta/Elev= 30
       0 1749.04   101.6 1734.08   150.8 1728.14   173.7 1726.79  327.861699.388
   386.8 1688.04   439.2 1676.19   521.2 1663.06   599.8    1662   639.2 1660.11
   754.61659.839   770.3 1658.19   780.1 1656.94   785.31658.203   789.9 1661.77
   796.5 1669.05     803 1673.68  833.561685.453   842.4  1689.7   858.7 1692.66
  871.691699.735   881.7 1704.21   911.2 1712.37   963.6 1725.05   986.5 1728.28
  1052.1 1733.14  1104.5 1738.78  1156.9 1740.88  1209.4  1739.4  1284.7 1731.24
#Mann= 7 ,-1 , 0
       0     .12       0  327.86     .06       0   754.6     .12       0
   770.3    .045       0   785.3     .12       0  833.56    .016       0
  871.69     .12       0
Bank Sta=770.3,785.3
XS Rating Curve= 0 ,0
Exp/Cntr=0.3,0.1

Type RM Length L Ch R = 1 ,11137.1 ,388,378.1,367.4
XS GIS Cut Line= 3
     2046081.634      220239.922     2045960.288      220589.387
     2045372.195      221205.933
#Sta/Elev= 30
       0  1762.6    58.9 1750.83   124.4 1734.07   157.1 1729.65   248.8 1711.49
  354.69 1696.44   386.3 1691.24   478.1 1669.17   543.6 1660.11   582.9 1658.67
  689.641658.538   700.9 1658.42   717.3 1656.21   727.1 1655.34  733.141656.133
   743.5 1661.96   769.7 1665.95  778.461668.448   789.4 1673.46   802.5 1676.75
  822.171690.023   861.5 1712.21   913.9 1739.29   943.4 1751.76     986  1766.8
  1028.6 1779.75  1061.4  1788.2  1123.7 1801.73  1176.1 1814.66    1222 1822.11
#Mann= 7 ,-1 , 0
       0     .12       0  354.69     .06       0  689.64     .12       0
   717.3    .045       0  733.14     .12       0  778.46    .016       0
  822.17     .12       0
#XS Ineff= 2 , 0
          566.36  1662.2
Permanent Ineff=
       F       F
Bank Sta=717.3,733.14
XS Rating Curve= 0 ,0
Exp/Cntr=0.3,0.1

Type RM Length L Ch R = 1 ,10759   ,284.3,280.5,276.5
XS GIS Cut Line= 3
     2045776.085       220069.16     2045600.495      220570.607
     2045246.388      221101.091
#Sta/Elev= 30
       0 1761.08    68.9 1749.85   124.6 1744.27   206.6 1726.98   226.3  1721.9
   255.8 1709.55   295.2 1696.82   331.2 1683.78   383.7 1673.42  416.371668.819
   498.5 1654.27   505.1 1653.76  513.451654.265  520.681656.119  526.941656.995
   577.1 1657.28   658.9 1663.19   706.71672.141   717.7 1676.23   727.6 1677.48
   740.6 1685.48   747.31688.642   822.4 1725.55   851.8 1738.97   923.8 1767.93
   959.8 1778.85   982.7 1783.79  1008.8  1787.1  1093.9 1793.33  1169.1 1801.47
#Mann= 8 ,-1 , 0
       0     .12       0  416.37     .06       0   498.5    .045       0
  513.45     .06       0  520.68     .12       0  526.94     .06       0
   706.7    .016       0   747.3     .12       0
Bank Sta=498.5,513.45
XS Rating Curve= 0 ,0
Exp/Cntr=0.3,0.1

Type RM Length L Ch R = 1 ,10478.5 ,374.8,376.4,375
XS GIS Cut Line= 3
     2045428.797       219948.12     2045334.075      220516.673
     2045215.742      221044.197
#Sta/Elev= 30
       0 1766.84    65.5  1745.8   108.1 1738.69   144.1 1728.82   291.5 1675.79
  373.431672.085   451.9 1666.13   504.3 1664.24   510.9 1662.72  520.451656.286
  526.67 1652.73   530.5 1652.07   540.4 1652.69   550.2  1655.2  568.73 1655.15
  569.941655.119   612.4 1657.72   625.5 1661.38  640.461668.944   651.8 1675.49
   671.4 1679.89  692.69  1694.8   763.2 1730.85   822.1 1753.34   851.6 1762.79
   897.5 1771.28   953.2 1777.03  1012.2 1779.71  1044.9 1776.64    1117 1793.12
#Mann= 9 ,-1 , 0
       0     .12       0  373.43     .06       0  520.45     .12       0
  526.67    .045       0   540.4     .12       0  568.73     .06       0
  569.94     .12       0  640.46    .016       0  692.69     .12       0
Bank Sta=526.67,540.4
XS Rating Curve= 0 ,0
Exp/Cntr=0.3,0.1

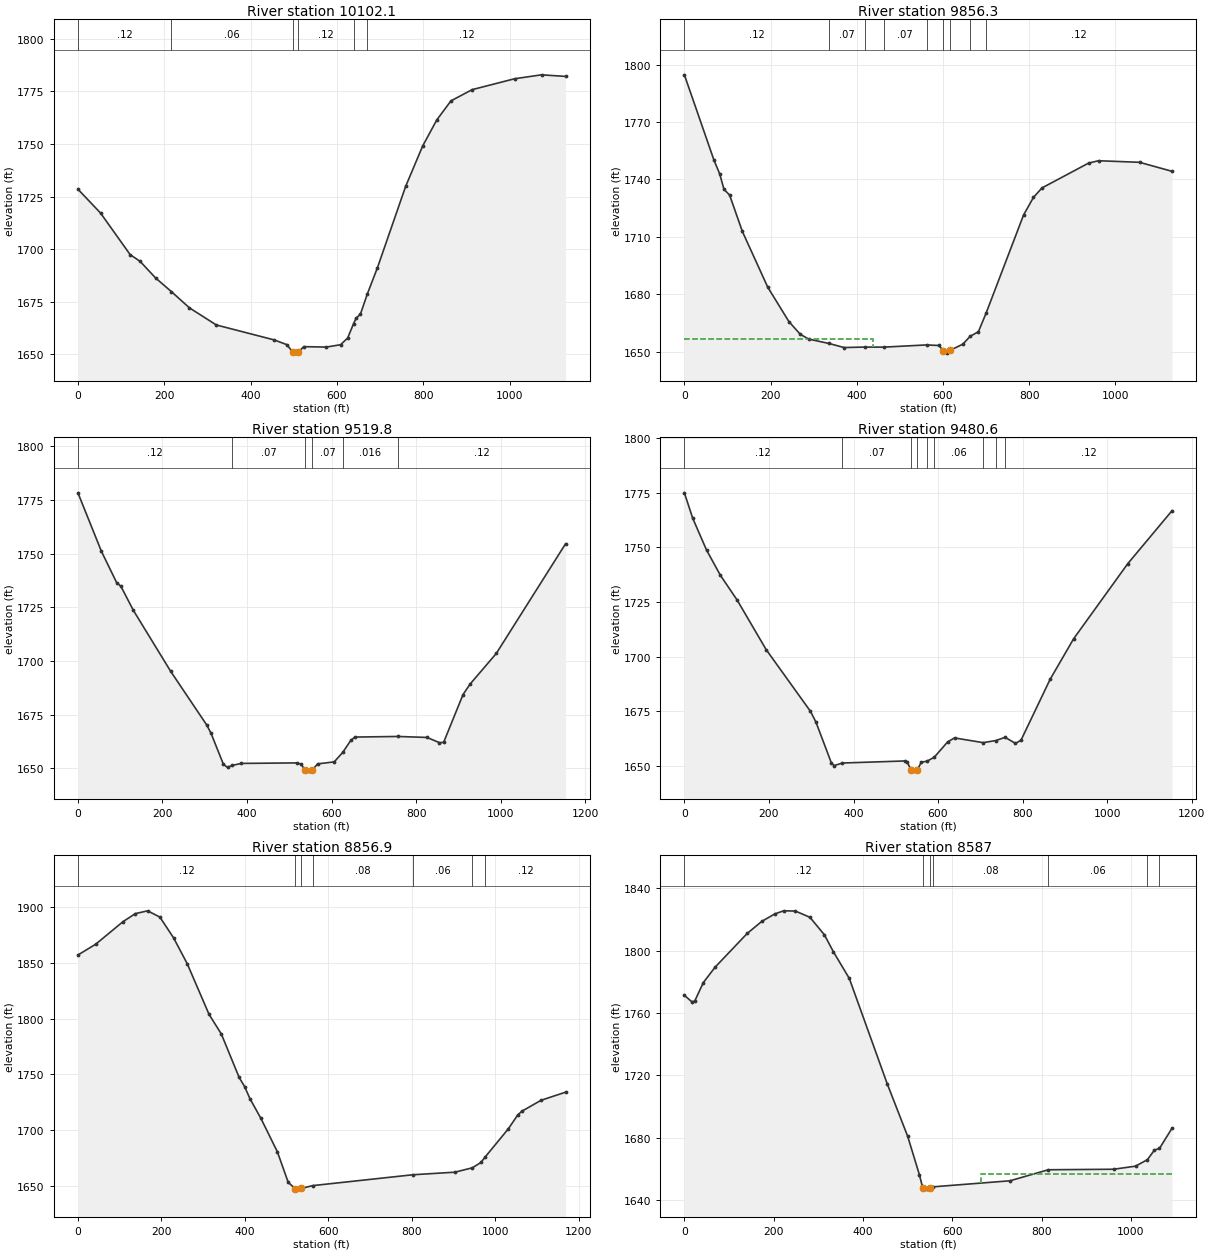
Type RM Length L Ch R = 1 ,10102.1 ,247.5,245.8,244.3
XS GIS Cut Line= 3
     2045108.328      219899.395     2044984.849      220471.573
     2044931.579      221012.946
#Sta/Elev= 30
       0 1728.47    52.3 1717.17     121  1697.4   143.9 1694.24   179.9 1686.33
  216.611679.825   258.3 1672.13   320.5 1664.02   454.6 1656.92     484 1654.66
   497.1 1651.21   503.6 1650.65   510.1 1651.18   523.2 1653.72   575.5 1653.53
   608.3 1654.64   624.7 1657.83  638.431664.663   644.3 1667.25   654.2 1669.12
  670.46 1678.86   693.5  1691.1     759 1729.81   798.4 1748.99   831.1 1761.35
   863.9  1770.4     913 1775.73  1011.4  1780.9  1073.6 1782.76  1129.3 1782.01
#Mann= 6 ,-1 , 0
       0     .12       0  216.61     .06       0   497.1    .045       0
   510.1     .12       0  638.43    .016       0  670.46     .12       0
Bank Sta=497.1,510.1
XS Rating Curve= 0 ,0
Exp/Cntr=0.3,0.1

Type RM Length L Ch R = 1 ,9856.3  ,333.5,336.5,337.7
XS GIS Cut Line= 2
     2044833.805      219816.745     2044707.937      220940.877
#Sta/Elev= 30
       0 1794.64    68.8 1749.93      82 1742.82    91.8 1734.81   104.9 1731.81
   134.4 1712.82   193.4 1683.63   242.6 1665.62   268.8 1659.04   288.5  1656.5
   335.51654.227   370.5  1652.1  418.461652.353  461.991652.308  561.78 1653.47
   590.2 1653.17   600.9 1650.48   609.8 1649.18   615.9 1650.59   645.9 1653.86
  662.861657.957     682 1660.35  699.881670.069   786.9 1721.41   809.8 1730.58
   829.5 1735.52   937.7 1748.51   960.7 1749.74  1055.8 1748.92  1131.2 1744.21
#Mann= 9 ,-1 , 0
       0     .12       0   335.5     .07       0  418.46     .06       0
  461.99     .07       0  561.78     .12       0   600.9    .045       0
   615.9     .12       0  662.86    .016       0  699.88     .12       0
#XS Ineff= 2 , 0
          438.14 1656.55
Permanent Ineff=
       F       F
Bank Sta=600.9,615.9
XS Rating Curve= 0 ,0
Exp/Cntr=0.3,0.1

Type RM Length L Ch R = 1 ,9519.8  ,39.2,39.2,39.2
XS GIS Cut Line= 2
      2044599.43       219742.96     2044371.565      220873.603
#Sta/Elev= 30
       0 1778.31    55.7 1751.01    91.8 1736.42   101.6 1734.82   131.1  1723.6
   219.5 1695.17   304.7 1670.21   314.6 1666.47     344 1651.99   353.9 1650.44
  363.931651.377   386.6 1652.33   517.7 1652.57   527.5 1652.02   537.4 1649.25
   547.2 1648.74   553.8 1649.14   566.9 1652.11   606.2 1653.05  626.671657.523
   645.5 1663.08   655.3  1664.6  756.92 1664.88   825.7 1664.42   855.2 1661.99
     865 1662.13   910.9 1684.38   927.3  1689.2   989.5 1703.51  1153.4 1754.59
#Mann= 6 ,-1 , 0
       0     .12       0  363.93     .07       0   537.4    .045       0
   553.8     .07       0  626.67    .016       0  756.92     .12       0
Bank Sta=537.4,553.8
XS Rating Curve= 0 ,0
Exp/Cntr=0.3,0.1

Type RM Length L Ch R = 1 ,9480.6  ,627.3,623.7,616.1
XS GIS Cut Line= 2
     2044560.367       219738.62     2044332.502      220869.262
#Sta/Elev= 30
       0 1775.07    19.7 1763.41    52.4 1748.82    85.2 1737.24   124.5 1725.98
   193.3  1703.2   298.2 1674.87   311.3 1669.88   347.3 1651.39   353.9 1649.95
  373.551651.161     521  1652.1   527.5  1651.4  536.591647.802   540.6 1647.44
   550.5 1647.77   560.3 1651.54  573.771651.978  591.02 1653.81   622.6 1660.83
   638.9 1662.67  706.781660.503  736.911661.475  758.621662.946   783.1 1660.16
   796.2 1661.61     865 1689.52   920.7 1708.15  1048.5 1742.52  1153.4 1766.87
#Mann= 9 ,-1 , 0
       0     .12       0  373.55     .07       0  536.59    .045       0
   550.5     .07       0  573.77    .016       0  591.02     .06       0
  706.78     .12       0  736.91    .016       0  758.62     .12       0
Bank Sta=536.59,550.5
XS Rating Curve= 0 ,0
Exp/Cntr=0.3,0.1

Type RM Length L Ch R = 1 ,8856.9  ,266.1,269.9,273
XS GIS Cut Line= 2
     2044108.978      219469.523     2044056.895      220637.057
#Sta/Elev= 30
       0 1857.11    42.6  1866.8     108 1887.05   137.5 1894.26     167 1896.79
   196.4 1891.16   229.2 1872.56   261.9 1849.36   314.3 1803.78   343.7 1786.19
   386.3 1747.26   399.4 1738.98   412.5 1727.96   438.7 1710.29     478 1680.39
   504.1 1652.87   520.5 1647.38   527.1 1646.85  535.131647.454   562.71649.999
  802.991659.765   903.5 1662.07  945.591666.039   965.7 1670.78  976.491675.907
  1031.2 1700.84  1054.1 1713.42  1063.9 1716.78  1109.8 1726.61  1168.7 1733.91
#Mann= 7 ,-1 , 0
       0     .12       0   520.5    .045       0  535.13     .12       0
   562.7     .08       0  802.99     .06       0  945.59    .016       0
  976.49     .12       0
Bank Sta=520.5,535.13
XS Rating Curve= 0 ,0
Exp/Cntr=0.3,0.1

Type RM Length L Ch R = 1 ,8587    ,302.2,293.7,285.9
XS GIS Cut Line= 3
     2043928.569      219445.832     2043816.809      219980.245
     2043716.218      220517.201
#Sta/Elev= 30
       0 1771.33    16.4 1767.25    22.9 1767.49    42.5 1779.56    68.7 1789.38
   140.6 1811.05   173.3  1818.8   202.7 1823.63   222.3  1825.6   248.5 1825.46
   281.2 1821.45   313.8 1810.14   333.5 1799.44   369.4 1782.19   454.4 1714.48
   500.2 1680.79   526.4 1656.14   532.9 1648.75  534.781647.821   542.7 1646.88
   549.2  1647.8  556.261648.336   729.2 1652.23  815.131659.318   961.4 1659.65
  1010.5 1661.62 1037.231665.816    1053 1671.99 1064.241673.005  1092.3    1686
#Mann= 7 ,-1 , 0
       0     .12       0  534.78    .045       0   549.2     .12       0
  556.26     .08       0  815.13     .06       0 1037.23    .016       0
 1064.24     .12       0
#XS Ineff= 2 , 0
                          663.69          1656.3
Permanent Ineff=
       F       F
Bank Sta=534.78,549.2
XS Rating Curve= 0 ,0
Exp/Cntr=0.3,0.1

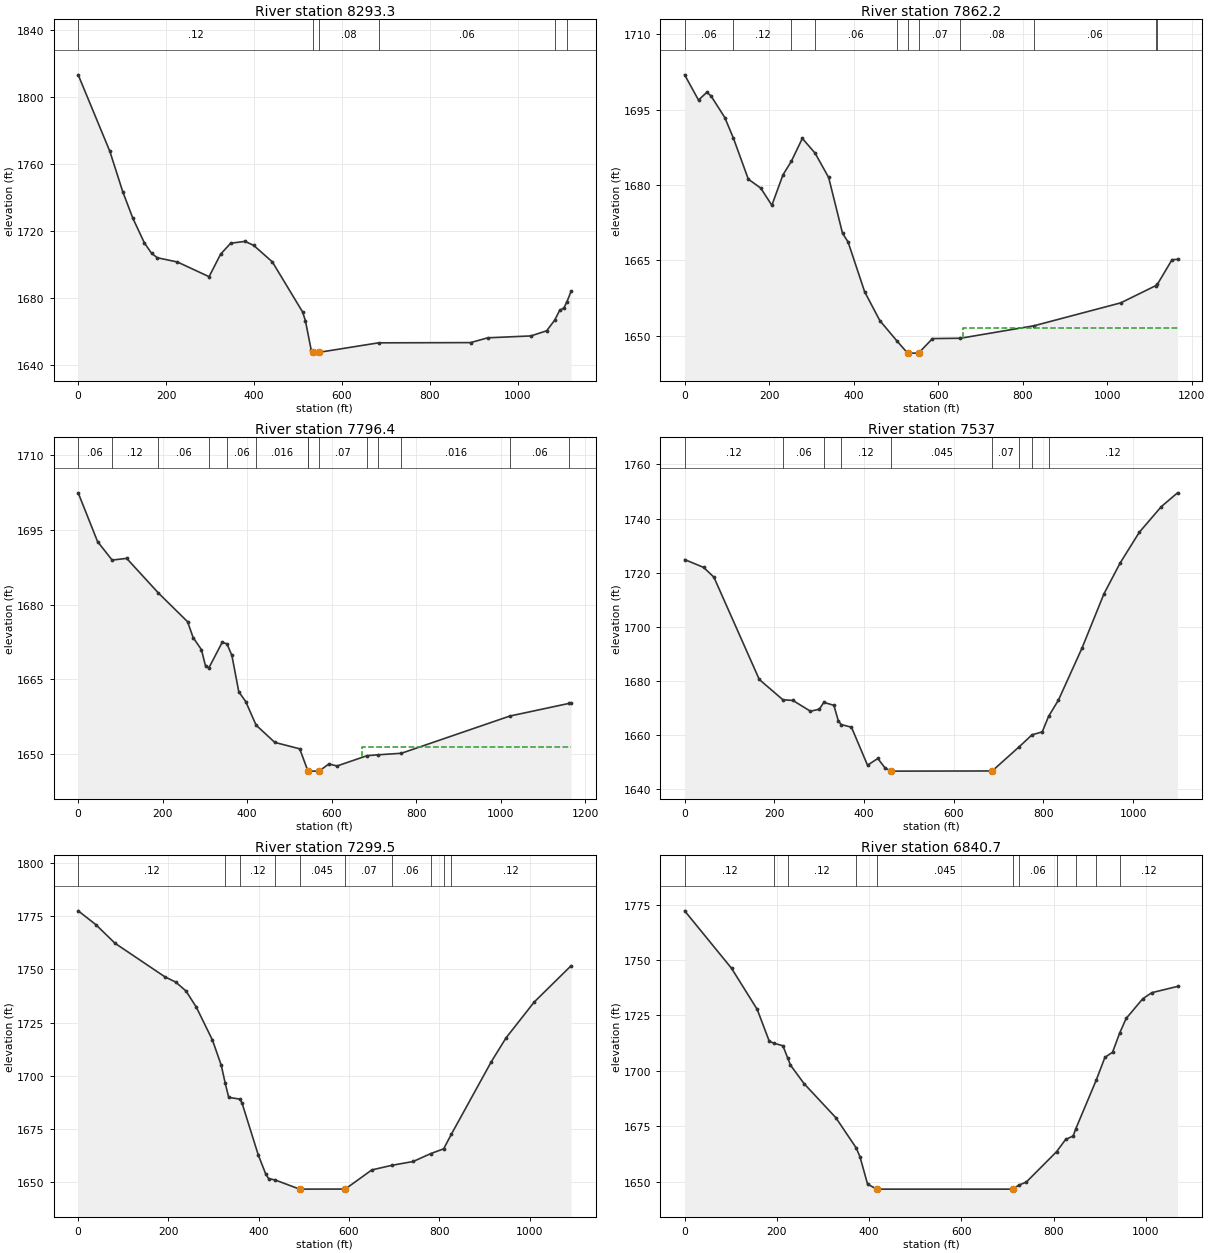
Type RM Length L Ch R = 1 ,8293.3  ,436.1,431,424.2
XS GIS Cut Line= 3
     2043432.887      219404.682     2043526.986      219936.206
      2043617.96      220510.237
#Sta/Elev= 30
       0 1813.17      72  1767.5   101.4 1743.36   124.3 1727.55   150.5 1712.86
   166.8 1706.64   179.9 1703.96   225.7 1701.42   297.7 1692.64   323.9 1706.08
   346.8 1712.63   379.5 1713.72   399.1 1711.35   441.6 1701.48   510.4 1671.58
   516.9 1666.23     530 1648.78   533.2 1647.48     543    1647  547.531647.467
  683.061653.147   892.4 1653.28   931.6 1656.15  1029.6 1657.27  1065.5 1660.34
 1083.881666.725  1094.9 1672.47  1104.7    1674 1111.78  1677.8    1121 1683.84
#Mann= 6 ,-1 , 0
       0     .12       0   533.2    .045       0  547.53     .08       0
  683.06     .06       0 1083.88    .016       0 1111.78     .08       0
Bank Sta=533.2,547.53
XS Rating Curve= 0 ,0
Exp/Cntr=0.3,0.1

Type RM Length L Ch R = 1 ,7862.2  ,66.1,65.8,66.3
XS GIS Cut Line= 2
     2042921.912       219588.88     2043401.513      220652.248
#Sta/Elev= 30
       0 1701.91    32.8 1696.89    52.4 1698.43    62.3 1697.73      95 1693.42
  115.581689.272   150.7 1681.16   180.2 1679.38   206.4 1675.96   232.6 1682.01
  252.621684.737   278.5 1689.27   308.61686.352   340.8  1681.5   373.6 1670.41
   386.7 1668.69     426 1658.77     462 1653.03  503.031648.935   527.6 1646.58
   530.8 1646.57   553.6 1646.57   586.5 1649.46  652.831649.529  827.071652.015
  1032.2 1656.57  1114.71659.976 1118.711660.246  1153.4 1665.14  1166.5 1665.22
#Mann= 11 ,-1 , 0
       0     .06       0  115.58     .12       0  252.62     .08       0
   308.6     .06       0  503.03     .12       0   527.6    .045       0
   553.6     .07       0  652.83     .08       0  827.07     .06       0
  1114.7     .12       0 1118.71    .016       0
#XS Ineff= 2 , 0
                          658.73         1651.47
Permanent Ineff=
       F       F
Bank Sta=527.6,553.6
XS Rating Curve= 0 ,0
Exp/Cntr=0.3,0.1

Type RM Length L Ch R = 1 ,7796.4  ,250.8,259.5,271.1
XS GIS Cut Line= 2
     2042858.978      219608.412     2043338.579       220671.78
#Sta/Elev= 30
       0 1702.46    45.9 1692.66    80.41688.954   114.7  1689.3   189.91682.339
   258.9 1676.58     272  1673.4   291.6 1670.98   301.5 1667.65  309.311667.311
   340.8 1672.43  351.981672.136   363.7 1669.84   380.1 1662.51   396.5 1660.54
  421.061655.808   465.3 1652.34   524.3 1651.05  543.161646.717   543.9 1646.62
   547.2 1646.57   570.2 1646.58   593.1    1648   612.8 1647.61  683.751649.673
  708.431649.842  764.881650.156 1021.361657.625 1162.09 1660.18  1166.5 1660.23
#Mann= 14 ,-1 , 0
       0     .06       0    80.4     .12       0   189.9     .06       0
  309.31     .08       0  351.98     .06       0  421.06    .016       0
  543.16     .12       0   543.9    .045       0   570.2     .07       0
  683.75    .016       0  708.43     .08       0  764.88    .016       0
 1021.36     .06       0 1162.09     .12       0
#XS Ineff= 2 , 0
                          672.82         1651.35
Permanent Ineff=
       F       F
Bank Sta=543.9,570.2
XS Rating Curve= 0 ,0
Exp/Cntr=0.3,0.1

Type RM Length L Ch R = 1 ,7537    ,235,237.5,236.4
XS GIS Cut Line= 3
     2042813.266       219619.19     2042840.577      220173.173
     2042785.909      220714.894
#Sta/Elev= 30
       0 1724.83    42.4 1721.92    65.2 1718.32   166.4 1680.48  219.161672.955
   241.4 1672.72   280.6 1668.72   300.2 1669.48  310.451672.014   332.8  1670.9
   342.6 1665.22  348.841663.814     372 1662.81   407.8 1648.76   430.7 1651.25
     447 1647.72     460 1646.61   463.3 1646.57   685.8 1646.63  746.591655.667
  774.611659.999   797.4 1661.08  811.641666.859   833.4  1672.8   885.9 1692.02
   935.1 1712.17   971.2 1723.58  1013.8 1734.91    1063 1744.42  1099.1 1749.51
#Mann= 9 ,-1 , 0
       0     .12       0  219.16     .06       0  310.45    .016       0
  348.84     .12       0     460    .045       0   685.8     .07       0
  746.59     .06       0  774.61    .016       0  811.64     .12       0
Bank Sta=460,685.8
XS Rating Curve= 0 ,0
Exp/Cntr=0.3,0.1

Type RM Length L Ch R = 1 ,7299.5  ,452.2,458.8,465.3
XS GIS Cut Line= 3
     2042635.925       219593.44     2042605.105       220138.57
     2042574.286      220683.699
#Sta/Elev= 30
       0  1777.6    39.2 1771.09    81.7 1762.32   192.9 1746.42   215.8 1744.09
   238.7  1739.9   261.6 1732.31   297.5 1716.74   317.1  1704.8  325.771696.417
   333.5 1689.77  358.271688.949   362.9 1687.17   398.9 1662.73   415.2 1653.85
   421.8 1651.53  435.971650.912   490.4 1646.58   493.7 1646.57   591.8 1646.61
   650.6 1655.62  694.821657.777   742.2 1659.58  780.971663.287  809.721665.539
  826.621672.359   915.4 1706.61   948.1 1717.83  1010.3 1734.65    1092 1751.73
#Mann= 10 ,-1 , 0
       0     .12       0  325.77    .016       0  358.27     .12       0
  435.97     .07       0   490.4    .045       0   591.8     .07       0
  694.82     .06       0  780.97    .016       0  809.72     .06       0
  826.62     .12       0
Bank Sta=490.4,591.8
XS Rating Curve= 0 ,0
Exp/Cntr=0.3,0.1

Type RM Length L Ch R = 1 ,6840.7  ,254,246.1,237.9
XS GIS Cut Line= 2
     2042316.443      219632.283      2041951.86      220637.057
#Sta/Elev= 30
       0 1772.27   101.6 1746.33   157.4 1727.73   183.6 1713.32  194.461712.407
   213.1 1711.32  223.161705.997   229.5 1702.58     259 1694.22   327.9 1678.83
  372.051665.192   380.3 1661.14   396.7 1648.81   416.4 1646.62   419.7 1646.57
   711.5 1646.57  724.391648.329     741 1649.77  806.561663.479   826.2    1669
   842.6  1670.6  848.151673.771  892.431695.729   911.5 1706.12   927.9 1708.37
  943.291716.999   957.4 1723.64   993.5 1732.56  1013.1  1735.3  1068.9 1738.13
#Mann= 11 ,-1 , 0
       0     .12       0  194.46    .016       0  223.16     .12       0
  372.05     .07       0   416.4    .045       0   711.5     .04       0
  724.39     .06       0  806.56    .016       0  848.15     .12       0
  892.43    .016       0  943.29     .12       0
Bank Sta=416.4,711.5
XS Rating Curve= 0 ,0
Exp/Cntr=0.3,0.1

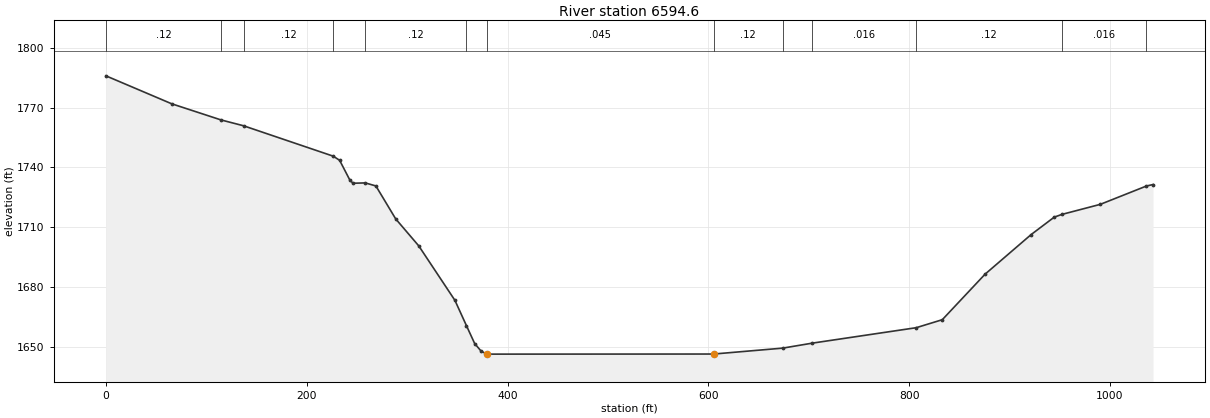
Type RM Length L Ch R = 1 ,6594.6  ,210,203.1,196.1
XS GIS Cut Line= 2
     2041921.019      219580.182     2041927.404      220623.024
#Sta/Elev= 30
       0 1785.86    65.6 1771.85  114.561763.803  137.071760.865  226.461745.639
   232.8 1743.56   242.7 1733.94     246  1732.1  258.361732.267   268.9 1730.74
   288.6 1714.27   311.6 1700.74   347.6 1673.49  359.121660.784   367.3 1651.84
   373.9 1647.96   379.6 1646.65   380.4 1646.57   605.31646.616  673.981649.568
  703.52 1652.07  806.981659.792     833  1663.8   875.6 1686.59   921.5 1706.42
   944.5 1715.14  952.191716.509   990.4 1721.54 1036.351730.717  1042.9 1731.45
#Mann= 13 ,-1 , 0
       0     .12       0  114.56     .06       0  137.07     .12       0
  226.46    .016       0  258.36     .12       0  359.12     .07       0
   379.6    .045       0   605.3     .12       0  673.98     .06       0
  703.52    .016       0  806.98     .12       0  952.19    .016       0
 1036.35     .12       0
Bank Sta=379.6,605.3
XS Rating Curve= 0 ,0
Exp/Cntr=0.3,0.1