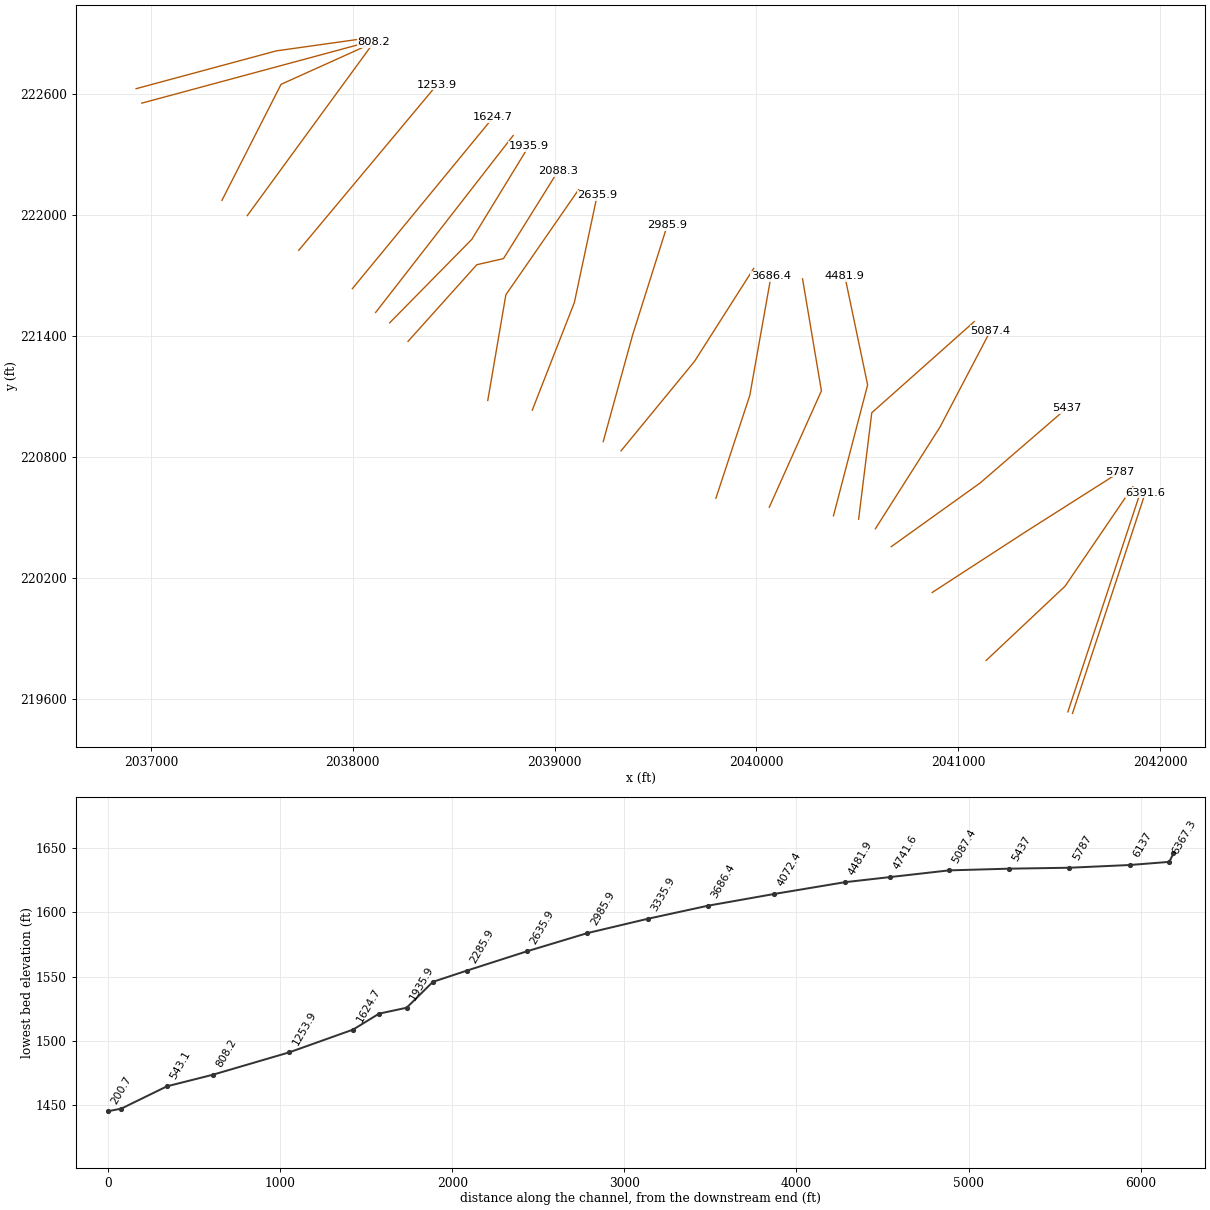
HEC-RAS study STONYCK.prj: STONYCK

--- STONYCK.g01 (geometry) --- (continued)

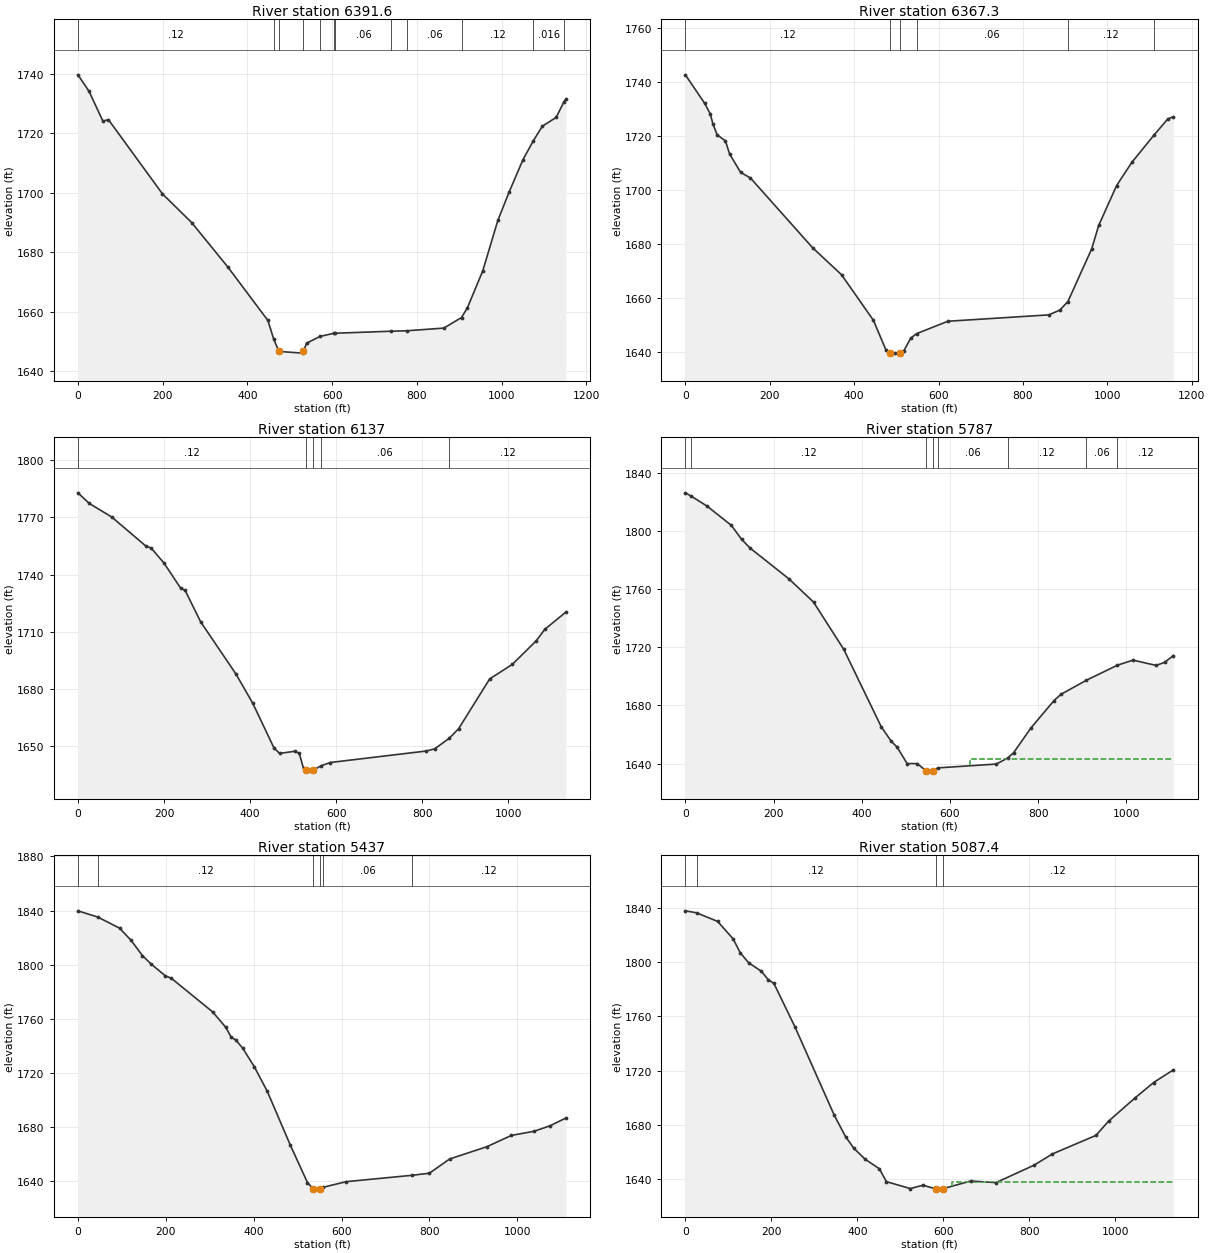
Type RM Length L Ch R = 1 ,6391.6  ,24.3,24.3,24.3
XS GIS Cut Line= 2
     2041566.357      219529.071     2041927.404      220623.024
#Sta/Elev= 30
       0 1739.59    26.2 1734.06    58.9 1724.04      72 1724.52   199.6 1699.56
   268.4 1689.94   353.4 1675.07   448.4 1657.02   462.51650.633   474.5  1646.6
   530.2 1646.03  532.07 1646.59     540 1649.39  571.581651.646  603.861652.696
  608.011652.726  740.051653.398  777.42 1653.55     864 1654.45  905.651658.006
   919.6 1661.31   955.6 1673.63   991.6 1690.75  1017.8 1700.11  1050.5 1711.02
 1075.371717.468  1096.4 1722.31  1129.1 1725.28 1147.311730.501    1152 1731.45
#Mann= 12 ,-1 , 0
       0     .12       0   462.5     .07       0   474.5    .045       0
  532.07     .07       0  571.58     .06       0  603.86     .12       0
  608.01     .06       0  740.05     .12       0  777.42     .06       0
  905.65     .12       0 1075.37    .016       0 1147.31     .12       0
Bank Sta=474.5,532.07
XS Rating Curve= 0 ,0
Exp/Cntr=0.3,0.1

Type RM Length L Ch R = 1 ,6367.3  ,241.5,230.3,224
XS GIS Cut Line= 2
      2041543.44      219536.363     2041905.853      220634.453
#Sta/Elev= 30
       0 1742.77    45.9 1732.16      59 1728.25    65.5 1724.46    75.3 1720.51
      95 1718.22   104.8 1713.39     131 1706.53     154  1704.5   301.4 1678.58
   370.2 1668.52   445.5 1651.65     475 1640.75   484.8 1639.53   497.9 1639.43
   507.8  1639.6   517.6 1640.28     534 1644.96  547.931646.669   622.4 1651.27
   861.5 1653.64   887.7 1655.44  906.531658.572   963.1 1678.21   979.5 1686.83
    1022 1701.64  1058.1 1710.27 1111.721720.601  1143.2 1726.36  1156.4 1727.23
#Mann= 6 ,-1 , 0
       0     .12       0   484.8    .045       0   507.8     .07       0
  547.93     .06       0  906.53     .12       0 1111.72    .016       0
Bank Sta=484.8,507.8
XS Rating Curve= 0 ,0
Exp/Cntr=0.3,0.1

Type RM Length L Ch R = 1 ,6137    ,354,350,339.9
XS GIS Cut Line= 3
     2041138.516      219791.393      2041529.64      220159.509
     2041865.324      220652.444
#Sta/Elev= 30
       0 1782.81    26.2 1777.28    78.6 1770.12   157.2 1755.03   170.3 1753.83
   199.8 1746.03   239.1 1732.71   248.9 1731.72   284.9 1715.28   366.8 1687.96
   406.1 1672.55   455.2 1649.21   468.3 1646.26   504.4 1647.41   514.2 1646.22
     524 1638.41   530.6 1637.38   540.4 1636.98  545.561637.331  564.921639.796
   586.3  1641.5   809.1 1647.52   828.8 1648.67  862.37 1654.15   884.4 1659.24
   956.5  1685.3    1009 1692.91  1064.7 1705.29  1084.3 1711.24  1133.5 1720.31
#Mann= 5 ,-1 , 0
       0     .12       0   530.6    .045       0  545.56     .12       0
  564.92     .06       0  862.37     .12       0
Bank Sta=530.6,545.56
XS Rating Curve= 0 ,0
Exp/Cntr=0.3,0.1

Type RM Length L Ch R = 1 ,5787    ,348.7,350,353.1
XS GIS Cut Line= 3
     2040870.857      220128.137     2041336.439      220430.424
     2041801.892      220726.073
#Sta/Elev= 30
       0 1826.17   12.811823.972      49 1817.08   104.5 1803.75   127.4 1794.24
   146.9 1788.16   235.1 1766.96   290.6 1751.06   359.2 1718.56   444.1  1665.4
   466.9 1655.35     480 1651.43   502.9 1640.05   525.7 1640.02   545.3 1635.29
   558.4 1634.86   561.6 1635.12  572.381637.088   705.2 1639.72  730.671643.835
   744.4 1647.53   783.5 1664.49   835.7  1683.3     852 1687.72  908.941697.261
  979.771707.693  1015.2 1711.17  1067.4 1707.53  1086.9 1709.65  1106.5 1714.28
#Mann= 8 ,-1 , 0
       0     .06       0   12.81     .12       0   545.3    .045       0
   561.6     .12       0  572.38     .06       0  730.67     .12       0
  908.94     .06       0  979.77     .12       0
#XS Ineff= 2 , 0
                          645.12         1642.88
Permanent Ineff=
       F       F
Bank Sta=545.3,561.6
XS Rating Curve= 0 ,0
Exp/Cntr=0.3,0.1

Type RM Length L Ch R = 1 ,5437    ,340.5,349.5,357.2
XS GIS Cut Line= 3
     2040668.115      220355.198      2041108.59      220670.838
     2041538.953      221042.457
#Sta/Elev= 30
       0 1839.77   44.971835.187    94.7 1826.98   120.8    1818   146.9 1806.65
   166.5 1800.48   199.1 1791.68   212.2 1790.04   306.8 1765.02   336.2 1753.78
   349.3 1746.17   359.1 1744.41   375.4  1738.1   401.5 1724.47   430.9 1706.41
   483.1 1666.84   522.3    1639   535.4 1634.35   545.2 1634.13   551.7  1634.4
  558.851635.553   610.5 1639.65  760.82 1644.36     800 1645.91   845.8 1656.38
   930.8 1665.49   986.3  1673.8  1038.6 1676.92  1074.6 1680.97  1110.5 1686.68
#Mann= 6 ,-1 , 0
       0     .06       0   44.97     .12       0   535.4    .045       0
   551.7     .12       0  558.85     .06       0  760.82     .12       0
Bank Sta=535.4,551.7
XS Rating Curve= 0 ,0
Exp/Cntr=0.3,0.1

Type RM Length L Ch R = 1 ,5087.4  ,351.3,345.8,337.2
XS GIS Cut Line= 3
     2040589.551      220444.108     2040910.397      220949.186
     2041159.566      221424.606
#Sta/Elev= 30
       0 1837.57   26.071836.112    75.2 1829.75   111.2 1816.89   127.5  1806.8
   147.1 1799.37   176.6 1793.16   192.9 1786.86     206 1784.15     255 1752.14
   346.6 1687.02   372.8 1671.31   392.4  1662.7   418.5 1654.73   451.2 1647.81
   467.6 1638.32   523.2 1633.22   552.6 1635.68     582 1633.08   585.3  1632.8
   598.4 1633.08   663.8 1638.75   722.7  1637.6   811.1 1650.41   853.7 1658.68
   955.1 1672.33   984.6 1682.85  1046.8  1700.1  1089.3 1711.24  1135.1 1720.55
#Mann= 4 ,-1 , 0
       0     .06       0   26.07     .12       0     582    .045       0
   598.4     .12       0
#XS Ineff= 2 , 0
                          619.47         1637.89
Permanent Ineff=
       F       F
Bank Sta=582,598.4
XS Rating Curve= 0 ,0
Exp/Cntr=0.3,0.1

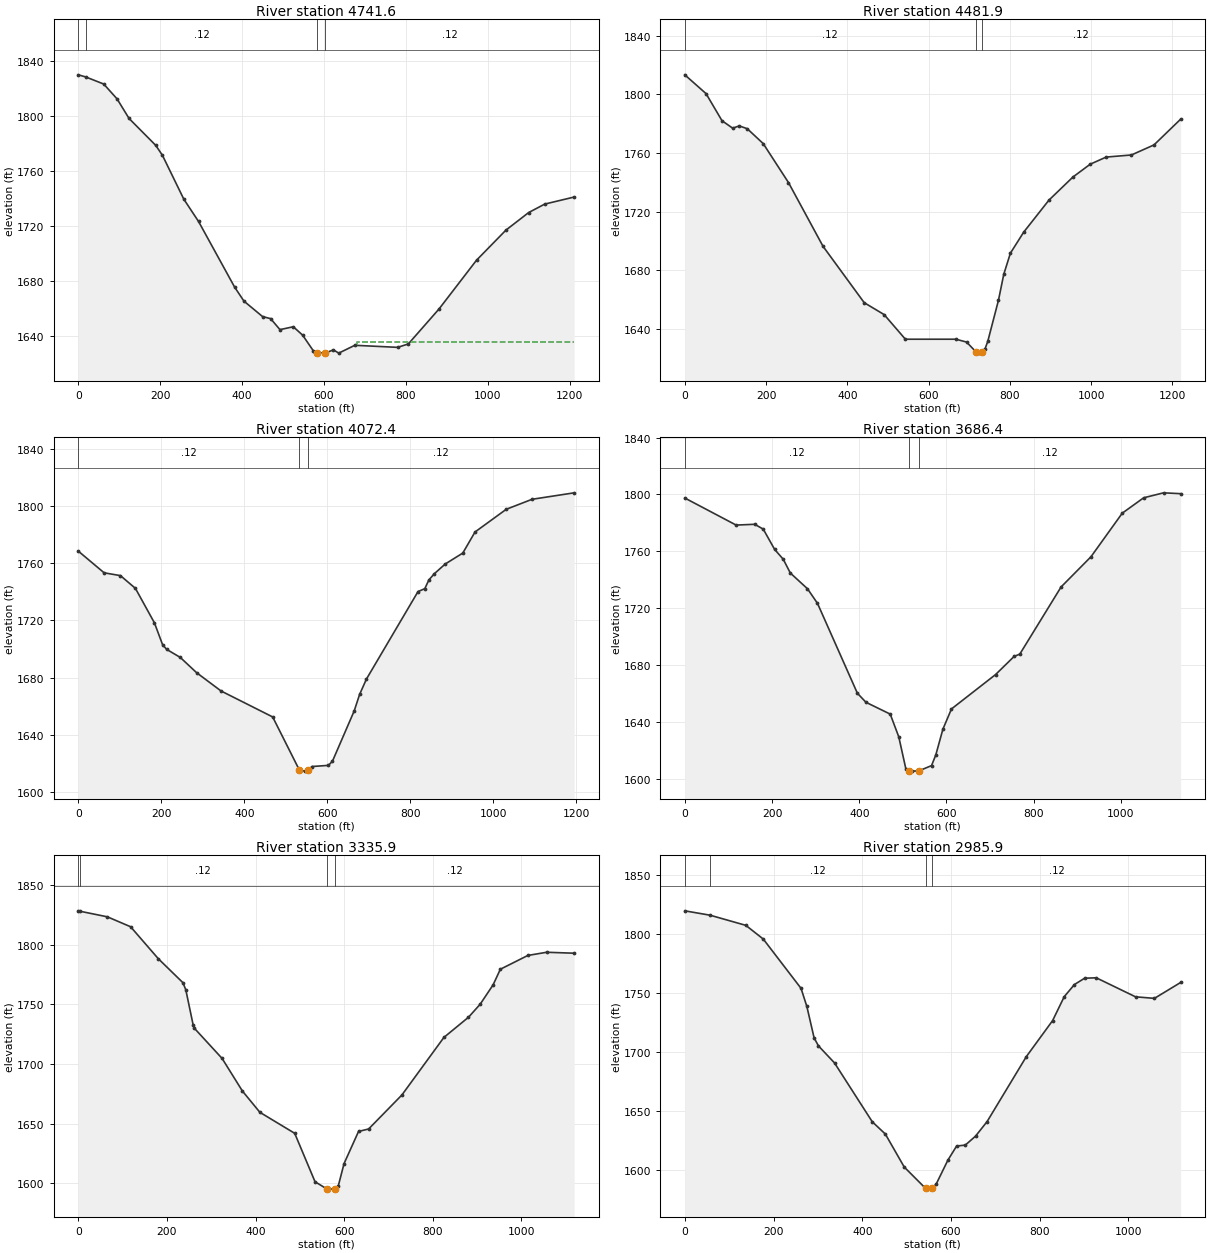
Type RM Length L Ch R = 1 ,4741.6  ,235.6,259.7,282.3
XS GIS Cut Line= 3
      2040506.51      220491.473     2040571.652      221019.002
     2041079.337      221470.377
#Sta/Elev= 30
       0  1829.8   18.091828.257      62 1823.11    94.6 1812.31   123.9 1798.07
   189.1 1778.52   205.4 1771.29   257.6 1739.42   293.5 1723.26   381.5 1675.61
   404.4 1665.34     450 1654.08   469.6  1652.6   492.4  1644.6     525  1646.7
   547.9 1640.56     574 1629.16   583.8 1627.71   603.4 1627.64     623  1629.9
     636 1627.53   675.2 1633.22   779.8 1631.73   805.9  1634.2     881 1659.66
   972.4 1695.04  1044.3 1716.94  1099.8  1729.7    1139 1735.85  1210.9 1740.98
#Mann= 4 ,-1 , 0
       0     .06       0   18.09     .12       0   583.8    .045       0
   603.4     .12       0
#XS Ineff= 2 , 0
                          680.64         1635.83
Permanent Ineff=
       F       F
Bank Sta=583.8,603.4
XS Rating Curve= 0 ,0
Exp/Cntr=0.3,0.1

Type RM Length L Ch R = 1 ,4481.9  ,420.8,409.5,395.3
XS GIS Cut Line= 3
     2040381.812      220508.133     2040551.083      221157.005
     2040438.236      221695.199
#Sta/Elev= 30
       0 1813.33    52.3 1800.52    91.6 1782.03   117.8 1776.96   134.1  1778.5
   153.7  1776.6     193 1766.44   255.2 1739.89   340.2 1696.43   441.6 1657.98
   490.7 1649.85     543 1633.06   667.3 1633.06   693.5 1631.13   716.4 1624.56
     723 1623.58  730.89 1624.66   739.3 1626.68   745.9 1631.71   772.1  1659.6
   785.2 1677.38   801.5 1691.73   834.2 1706.06   896.4 1727.91   955.4 1743.64
   997.9 1752.38  1037.2 1757.25  1099.4 1758.68    1155 1765.55  1220.5 1783.08
#Mann= 3 ,-1 , 0
       0     .12       0   716.4    .045       0  730.89     .12       0
Bank Sta=716.4,730.89
XS Rating Curve= 0 ,0
Exp/Cntr=0.3,0.1

Type RM Length L Ch R = 1 ,4072.4  ,383.1,385.9,389.9
XS GIS Cut Line= 3
     2040063.689      220550.586     2040322.086      221127.509
     2040228.557      221682.487
#Sta/Elev= 30
       0 1768.53    62.2 1753.35   101.5 1751.39   137.6 1742.45   183.4  1718.3
   203.1 1702.97   212.9 1699.71   245.6  1694.1     285  1683.4   343.9 1670.58
   468.4 1652.38  532.921615.063     547 1614.42  552.391615.035   563.4 1617.65
   602.7 1618.45   612.5 1621.39   664.9 1656.62     678 1668.22   694.3 1678.88
   818.7 1740.22     835 1742.24   844.8 1748.33   857.9 1752.69   884.1 1759.49
   926.6 1767.19   956.1 1781.96  1031.3 1797.85  1093.5 1804.86    1195 1809.39
#Mann= 3 ,-1 , 0
       0     .12       0  532.92    .045       0  552.39     .12       0
Bank Sta=532.92,552.39
XS Rating Curve= 0 ,0
Exp/Cntr=0.3,0.1

Type RM Length L Ch R = 1 ,3686.4  ,357.1,350.5,341.4
XS GIS Cut Line= 3
     2039799.314      220595.602     2039967.152      221105.033
     2040072.428      221696.219
#Sta/Elev= 30
       0  1797.5   117.7 1778.45   160.3    1779   179.9 1775.59     206  1761.3
   225.7  1754.4     242 1744.69   281.3 1733.62   304.2 1723.36   395.7 1660.07
   415.4  1653.7     471 1645.38   490.6 1629.37   506.9 1606.78   513.5 1605.38
     520 1605.25   536.4 1605.39   565.7 1609.14   575.5 1616.65   591.8 1634.81
   611.4 1649.02   712.6 1673.24     755 1685.98   768.1 1687.62   862.7 1734.88
   931.2 1756.13    1003 1786.83    1052 1797.65  1097.7 1801.15  1136.8 1800.55
#Mann= 3 ,-1 , 0
       0     .12       0   513.5    .045       0   536.4     .12       0
Bank Sta=513.5,536.4
XS Rating Curve= 0 ,0
Exp/Cntr=0.3,0.1

Type RM Length L Ch R = 1 ,3335.9  ,340.4,350,355.2
XS GIS Cut Line= 3
     2039329.164      220830.307     2039693.178      221273.692
     2039986.282      221733.787
#Sta/Elev= 30
       0  1828.6    2.99 1828.31    65.6 1823.56     118 1815.23   180.3  1788.5
     236 1768.32   242.6 1762.32     259 1733.13   262.2 1729.93   324.5 1704.72
   370.4 1677.33   409.8 1659.49   488.4 1641.87   534.3 1601.21   560.6 1595.27
   576.9 1595.02   580.2 1595.23   586.7 1597.59   599.8 1616.46   632.5 1643.43
   655.3  1645.5   730.5  1674.1   825.2 1722.35   880.7 1739.29   906.9 1750.14
   936.3  1766.5   952.6 1779.58  1014.7 1791.15  1057.1 1793.82  1119.2 1793.03
#Mann= 4 ,-1 , 0
       0     .06       0    2.99     .12       0   560.6    .045       0
   580.2     .12       0
Bank Sta=560.6,580.2
XS Rating Curve= 0 ,0
Exp/Cntr=0.3,0.1

Type RM Length L Ch R = 1 ,2985.9  ,351.6,350,351.8
XS GIS Cut Line= 3
      2039240.64      220875.798     2039386.909      221406.253
     2039557.927      221947.119
#Sta/Elev= 30
       0 1819.29      571815.589   137.6    1807   176.9  1795.4     262  1753.7
   275.1 1738.38   291.5 1711.73   301.3 1705.03   337.4 1690.66   422.5 1640.88
     452 1630.47   494.6 1602.56   542.8 1584.47     547 1583.89   557.8 1584.75
   566.6 1588.17   592.9 1608.36   612.6 1620.34   632.2 1621.13   655.2 1628.68
   681.4 1641.06   769.9 1696.06     829 1726.45   855.2  1746.7   878.2 1756.95
   901.1 1762.28   927.3 1762.65  1015.9 1746.55  1058.5 1745.25  1117.5 1758.68
#Mann= 4 ,-1 , 0
       0     .06       0      57     .12       0   542.8    .045       0
   557.8     .12       0
Bank Sta=542.8,557.8
XS Rating Curve= 0 ,0
Exp/Cntr=0.3,0.1

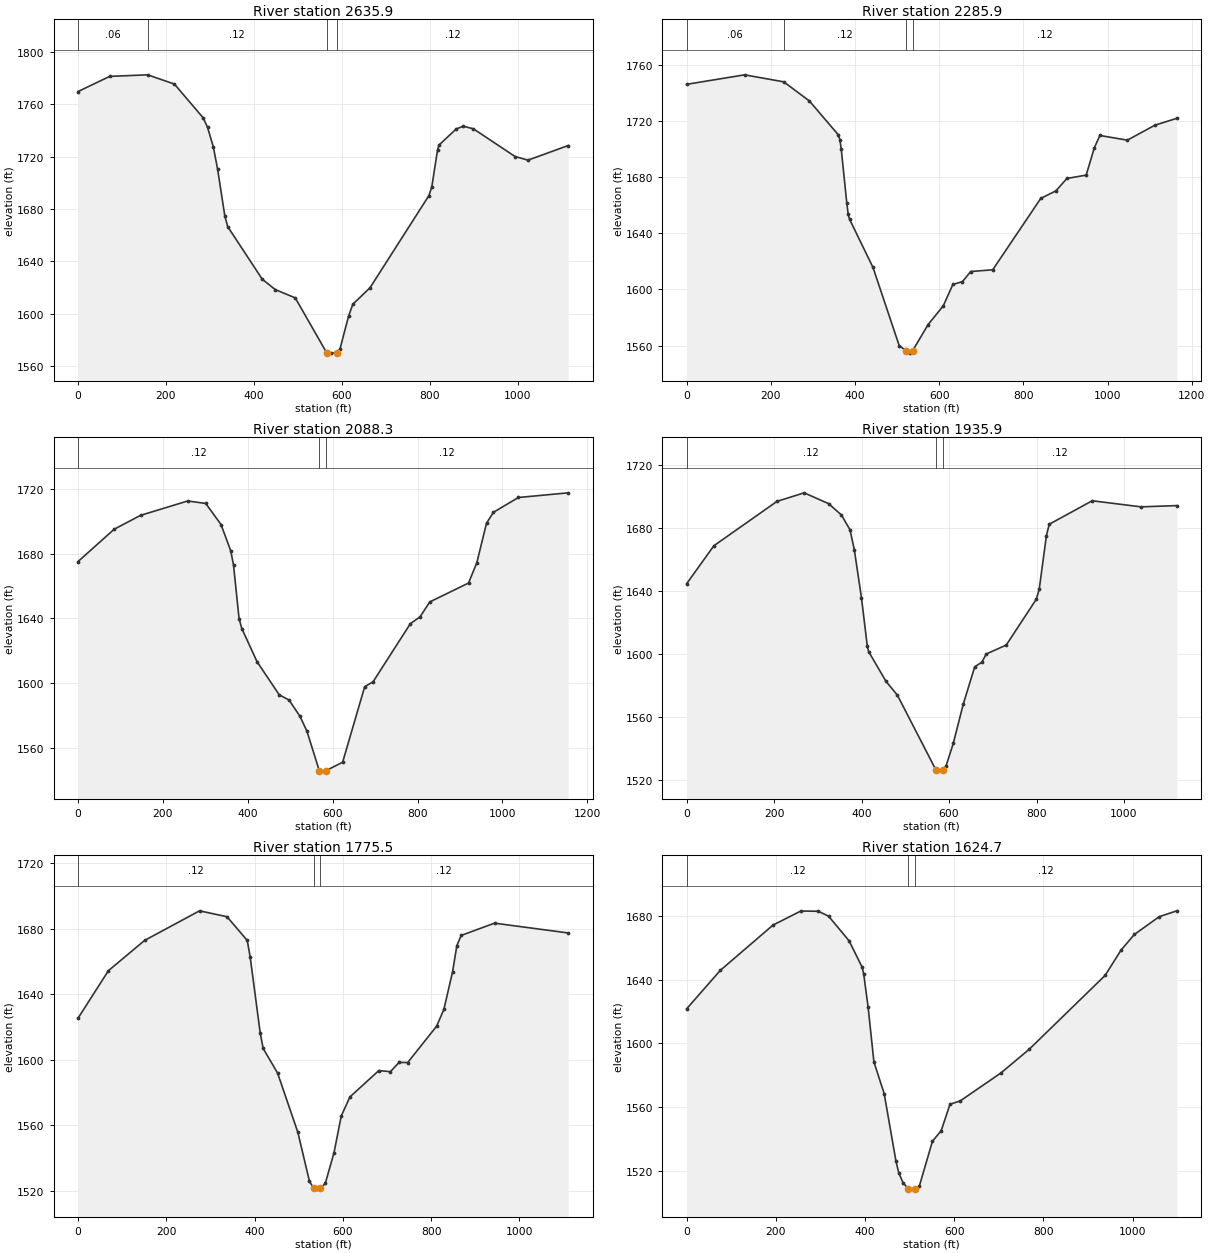
Type RM Length L Ch R = 1 ,2635.9  ,344.8,350,339.3
XS GIS Cut Line= 3
     2038889.136      221031.826      2039097.73       221565.39
      2039210.75      222095.887
#Sta/Elev= 30
       0 1769.87      72 1781.46  158.471782.654   219.3 1775.57   284.8 1749.69
   294.6 1742.53   307.7 1727.63   317.5 1710.61   333.9 1674.81   340.5 1666.52
     419 1626.35   448.5 1618.39   494.3 1611.99   565.4 1570.19   576.2 1569.74
   589.2 1569.79   595.8 1572.68   615.4 1597.86   625.2 1607.14   664.4 1619.78
   798.4  1690.3   804.9 1696.92     818 1725.22   821.2  1728.9   860.4 1741.24
   876.8 1743.33   899.6 1741.34   994.4 1720.16  1023.8 1717.38  1115.3 1728.58
#Mann= 4 ,-1 , 0
       0     .06       0  158.47     .12       0   565.4    .045       0
   589.2     .12       0
Bank Sta=565.4,589.2
XS Rating Curve= 0 ,0
Exp/Cntr=0.3,0.1

Type RM Length L Ch R = 1 ,2285.9  ,223.8,197.6,180.8
XS GIS Cut Line= 3
     2038668.592      221079.921     2038758.287      221603.655
     2039118.564      222124.405
#Sta/Elev= 30
       0 1745.96   137.8 1752.72  230.741747.727   291.9 1734.06   360.8 1709.88
   364.1  1706.6   367.4 1699.66   380.5 1661.59   383.8 1653.62     387    1650
   442.8 1615.63   505.1 1559.95   521.5 1556.39   531.4 1554.66  536.951556.367
   573.8 1575.01   609.7  1588.3   632.6 1603.55   655.4 1605.57     675 1612.75
   727.2 1613.95   841.4 1664.78   877.4 1670.15   903.5 1678.98   949.2 1681.34
   968.7  1700.8   981.8 1709.56  1047.1 1706.23  1112.4 1716.84  1164.6 1721.77
#Mann= 4 ,-1 , 0
       0     .06       0  230.74     .12       0   521.5    .045       0
  536.95     .12       0
Bank Sta=521.5,536.95
XS Rating Curve= 0 ,0
Exp/Cntr=0.3,0.1

Type RM Length L Ch R = 1 ,2088.3  ,139,152.4,170.3
XS GIS Cut Line= 4
     2038273.475      221372.735     2038614.187      221752.509
     2038746.565      221782.891     2039015.662      222214.748
#Sta/Elev= 30
       0 1675.06      85 1694.96   147.2 1703.53   258.4  1712.4   300.9 1710.88
   336.9 1697.85   359.8 1681.65   366.3 1672.94   379.4 1639.85   385.9 1633.74
   421.9 1613.25   474.2 1592.85   497.1 1589.73   523.1 1579.57   539.3 1570.48
   568.3 1546.23   571.6 1545.88   583.3 1546.07   623.4 1551.37   675.4 1597.95
     695 1600.91     783 1636.77   805.9    1641   828.7 1650.18     920 1661.81
   939.6 1674.36   962.4  1698.7   978.7 1705.42  1037.4 1714.54  1154.9 1717.42
#Mann= 3 ,-1 , 0
       0     .12       0   568.3    .045       0   583.3     .12       0
Bank Sta=568.3,583.3
XS Rating Curve= 0 ,0
Exp/Cntr=0.3,0.1

Type RM Length L Ch R = 1 ,1935.9  ,157.7,160.4,157.4
XS GIS Cut Line= 3
     2038182.504      221464.721     2038589.422      221878.168
      2038871.46      222339.369
#Sta/Elev= 30
       0  1644.5    62.3 1668.56   206.5 1696.69   268.8 1702.11   324.5 1695.26
     354 1688.06   373.6  1678.6   383.5 1665.84   399.8  1635.5     413 1605.04
   416.2 1601.44   455.6 1582.72   481.8 1573.89   570.3 1526.28   573.6 1525.71
   586.7 1526.22   593.2 1529.06   609.6 1543.23   632.5 1568.19   658.7 1591.84
   675.1 1594.78     685 1599.95   730.8 1605.63   799.6 1634.73   806.2  1641.1
   822.6 1675.04   829.1 1682.21   927.4 1697.08  1038.8 1693.22  1120.7 1694.02
#Mann= 3 ,-1 , 0
       0     .12       0   570.3    .045       0   586.7     .12       0
Bank Sta=570.3,586.7
XS Rating Curve= 0 ,0
Exp/Cntr=0.3,0.1

Type RM Length L Ch R = 1 ,1775.5  ,151.3,150.9,150.6
XS GIS Cut Line= 2
     2038112.884      221515.964     2038794.308        222392.7
#Sta/Elev= 30
       0 1625.46    68.8 1654.47   150.7 1672.93   275.2 1691.01   337.4 1687.42
   383.2 1672.97   389.8 1663.12   412.7 1616.35   419.3 1607.01     452 1591.96
   497.9  1555.8   524.1 1525.96   533.9 1521.56   540.5 1521.09  548.96 1521.56
   560.1 1524.58   579.8 1543.28   596.2  1565.7   615.8 1577.36   681.3 1593.47
   707.5 1592.79   727.2 1598.45   746.8 1598.39   812.3 1620.58   828.7  1630.8
   848.4 1653.76   858.2 1669.84     868 1675.99   943.4 1683.48  1110.4  1677.5
#Mann= 3 ,-1 , 0
       0     .12       0   533.9    .045       0  548.96     .12       0
Bank Sta=533.9,548.96
XS Rating Curve= 0 ,0
Exp/Cntr=0.3,0.1

Type RM Length L Ch R = 1 ,1624.7  ,371.1,370.8,369.3
XS GIS Cut Line= 2
     2037997.595      221633.944     2038695.512      222482.903
#Sta/Elev= 30
       0 1621.73    75.4 1645.82   193.6 1674.24   255.9 1683.06   295.3 1682.93
   318.2 1679.84   364.2 1664.41   393.7 1647.75     397 1643.54   406.8 1623.05
   419.9 1588.44   442.9 1568.58   469.1  1526.6   475.7 1518.78   485.5 1512.53
   496.71509.019   501.9 1508.66   511.8 1509.03   521.6 1510.42   551.1 1538.66
   570.8 1545.34   590.5 1561.89   613.5 1563.99   705.3 1581.65   767.7 1596.26
   938.3 1642.69   974.3 1658.68  1003.9 1668.38  1059.6 1679.52    1099 1683.19
#Mann= 3 ,-1 , 0
       0     .12       0   496.7    .045       0   511.8     .12       0
Bank Sta=496.7,511.8
XS Rating Curve= 0 ,0
Exp/Cntr=0.3,0.1

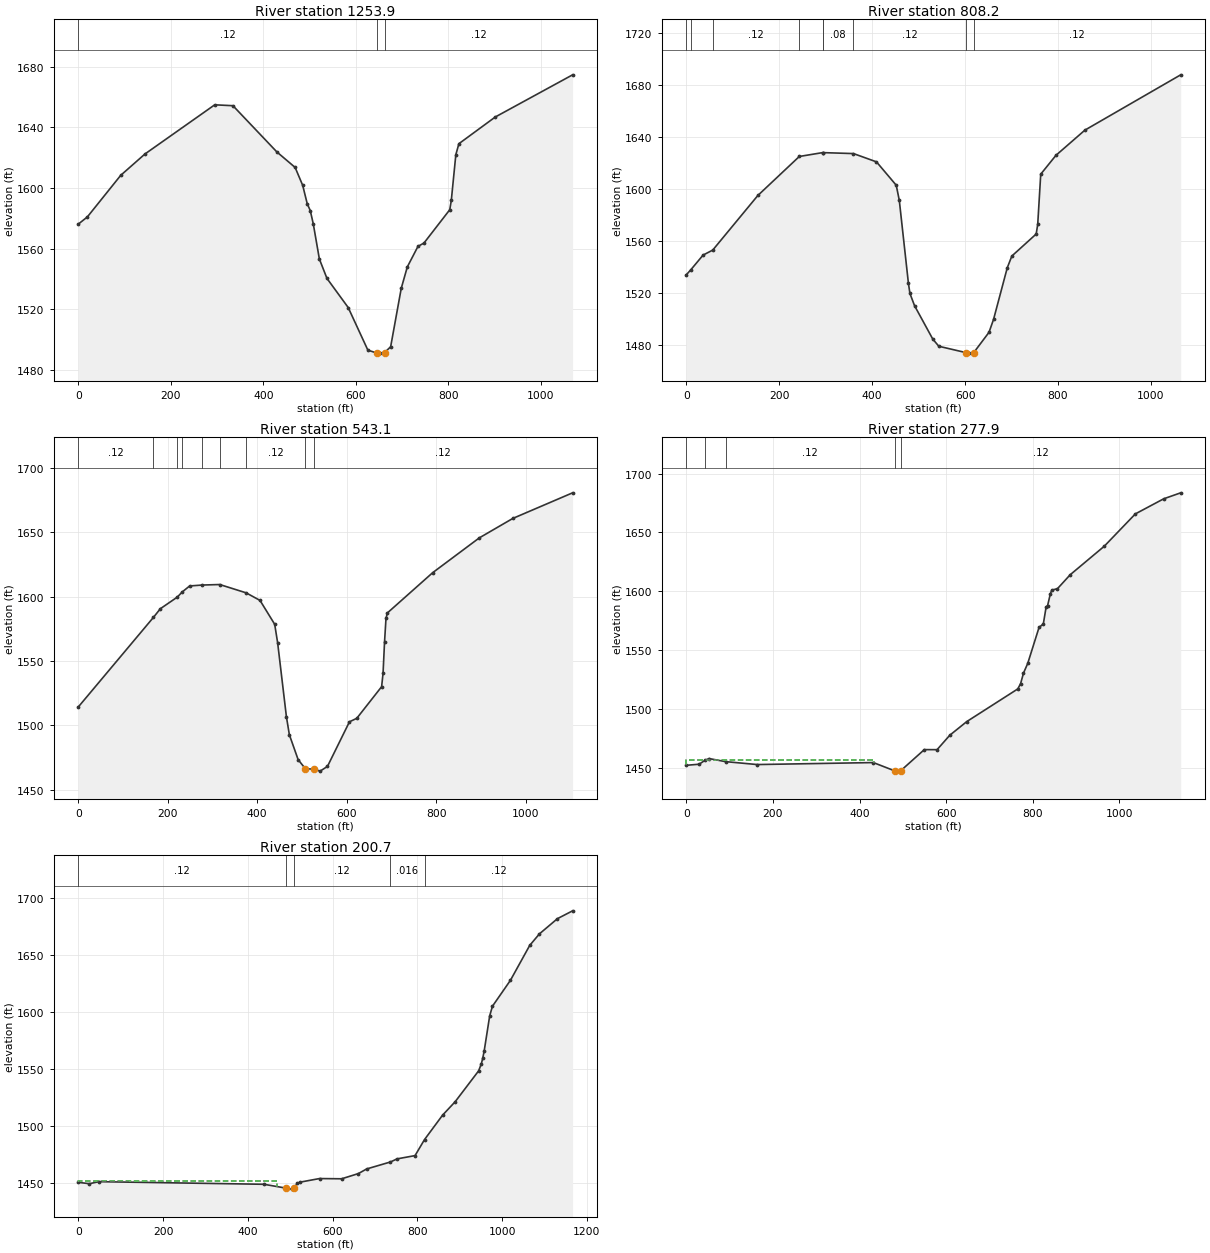
Type RM Length L Ch R = 1 ,1253.9  ,442.1,445.6,445.7
XS GIS Cut Line= 2
      2037731.97      221824.048     2038416.866      222644.361
#Sta/Elev= 30
       0 1576.09    19.7 1580.88    91.8 1608.34   144.2 1622.43     295  1654.9
   334.4 1654.31   429.4 1623.76   468.8 1613.55   485.2 1601.69     495 1589.54
   501.5  1585.1   508.1 1576.19   521.2 1553.09   537.6 1540.28   583.5 1521.05
   626.1 1492.87   645.8 1490.96   652.3 1490.93   662.2 1491.27   675.3 1495.16
   698.2  1533.7   711.3 1547.84   734.3 1561.39   747.4 1563.65   803.1 1585.63
   806.4 1591.75   816.2 1621.94   822.8 1629.21   901.5 1646.86  1068.6  1674.7
#Mann= 3 ,-1 , 0
       0     .12       0   645.8    .045       0   662.2     .12       0
Bank Sta=645.8,662.2
XS Rating Curve= 0 ,0
Exp/Cntr=0.3,0.1

Type RM Length L Ch R = 1 ,808.2   ,260.1,265.1,267.5
XS GIS Cut Line= 2
     2037476.762      221995.923     2038104.366      222855.298
#Sta/Elev= 30
       0 1533.71   10.07 1537.74      36 1548.83   56.811552.683   153.9 1594.68
  243.151624.692  293.381627.664  293.671627.659  359.791626.915   409.3 1620.54
   451.8 1602.58   458.4 1590.96     478 1527.26   481.3 1519.31   491.2 1509.92
   530.4 1484.26   543.5 1478.69   602.5 1473.75     609 1473.41   618.8 1473.88
   651.6 1489.46   661.4 1499.47   690.9 1539.13   700.7  1548.1   753.1 1565.04
   756.4 1572.45   762.9 1611.08   795.7 1625.59   857.9 1644.94  1064.2  1687.5
#Mann= 9 ,-1 , 0
       0     .12       0   10.07    .016       0   56.81     .12       0
  243.15    .016       0  293.38     .12       0  293.67     .08       0
  359.79     .12       0   602.5    .045       0   618.8     .12       0
Bank Sta=602.5,618.8
XS Rating Curve= 0 ,0
Exp/Cntr=0.3,0.1

Type RM Length L Ch R = 1 ,543.1   ,282.3,265.3,245
XS GIS Cut Line= 3
     2037351.166      222071.519     2037644.134      222646.606
     2038062.971      222835.408
#Sta/Elev= 30
       0 1514.28  167.981583.939   183.5 1590.69  221.15 1599.66  232.57 1603.78
     249 1608.38  277.351609.093  316.231609.482  375.111603.035   406.2 1597.14
     439 1578.59   445.6 1564.22   465.2 1506.75   471.8 1492.72   491.4 1473.37
   507.8 1466.23   525.9 1466.05   540.6 1464.44     557 1468.14   606.1 1502.78
   622.5 1505.51     678 1530.07   681.2 1540.52   684.5 1564.73   687.8 1583.27
     691 1587.44     792 1618.67   896.3 1645.75   971.2 1660.87  1104.8 1680.77
#Mann= 9 ,-1 , 0
       0     .12       0  167.98    .016       0  221.15     .12       0
  232.57    .016       0  277.35     .12       0  316.23     .06       0
  375.11     .12       0   507.8    .045       0   525.9     .12       0
Bank Sta=507.8,525.9
XS Rating Curve= 0 ,0
Exp/Cntr=0.3,0.1

Type RM Length L Ch R = 1 ,277.9   ,79.5,77.2,77.1
XS GIS Cut Line= 2
      2036954.03       222553.29     2038056.461      222850.599
#Sta/Elev= 30
       0 1452.01    29.4 1452.92   43.471456.337    52.4 1457.73   90.441455.134
   163.6 1452.64   431.9 1454.33   480.9 1447.32   487.5 1447.05  495.111447.389
   549.6 1465.34   579.1  1465.3   608.5 1477.59   647.8 1489.22   765.6 1516.98
   772.1 1521.57   778.7 1530.41   788.5 1538.68   814.6 1569.25   824.5  1572.2
     831 1586.73   834.3 1587.75   840.8 1597.93   844.1 1600.99   857.2 1602.23
   886.6 1614.07   965.2 1638.29  1037.1 1665.82  1102.6 1678.66  1141.8 1683.73
#Mann= 5 ,-1 , 0
       0     .12       0   43.47    .016       0   90.44     .12       0
   480.9    .045       0  495.11     .12       0
#XS Ineff= 2 , 0
          432.73 1456.76
Permanent Ineff=
       F       F
Bank Sta=480.9,495.11
XS Rating Curve= 0 ,0
Exp/Cntr=0.3,0.1

Type RM Length L Ch R = 1 ,200.7   ,206,200.7,195.2
XS GIS Cut Line= 3
     2036925.818      222624.905     2037620.645      222812.289
     2038062.971      222874.471
#Sta/Elev= 30
       0 1450.94    26.2 1449.79    49.1 1451.54   438.3 1449.25   490.7 1445.85
   503.8 1445.01  509.341445.913   516.8 1450.12   523.4 1451.13   569.2 1454.27
   621.5 1454.07   660.8 1458.62   680.4 1462.68  736.46 1468.79   752.2 1471.51
   794.6 1474.39  816.951488.427   859.8 1509.94   889.2 1521.57   944.6 1548.63
   951.1 1554.92   954.4 1559.89   957.7 1566.02   970.7 1596.83   977.2 1605.25
  1019.6 1627.94  1065.2 1658.58  1088.1 1668.66  1130.5 1681.97  1166.3 1688.84
#Mann= 5 ,-1 , 0
       0     .12       0   490.7    .045       0  509.34     .12       0
  736.46    .016       0  816.95     .12       0
#XS Ineff= 2 , 0
          468.57 1451.72
Permanent Ineff=
       F       F
Bank Sta=490.7,509.34
XS Rating Curve= 0 ,0
Exp/Cntr=0.3,0.1

Chan Stop Cuts=-1
Use User Specified Reach Order=0
Composite Channel Slope=5